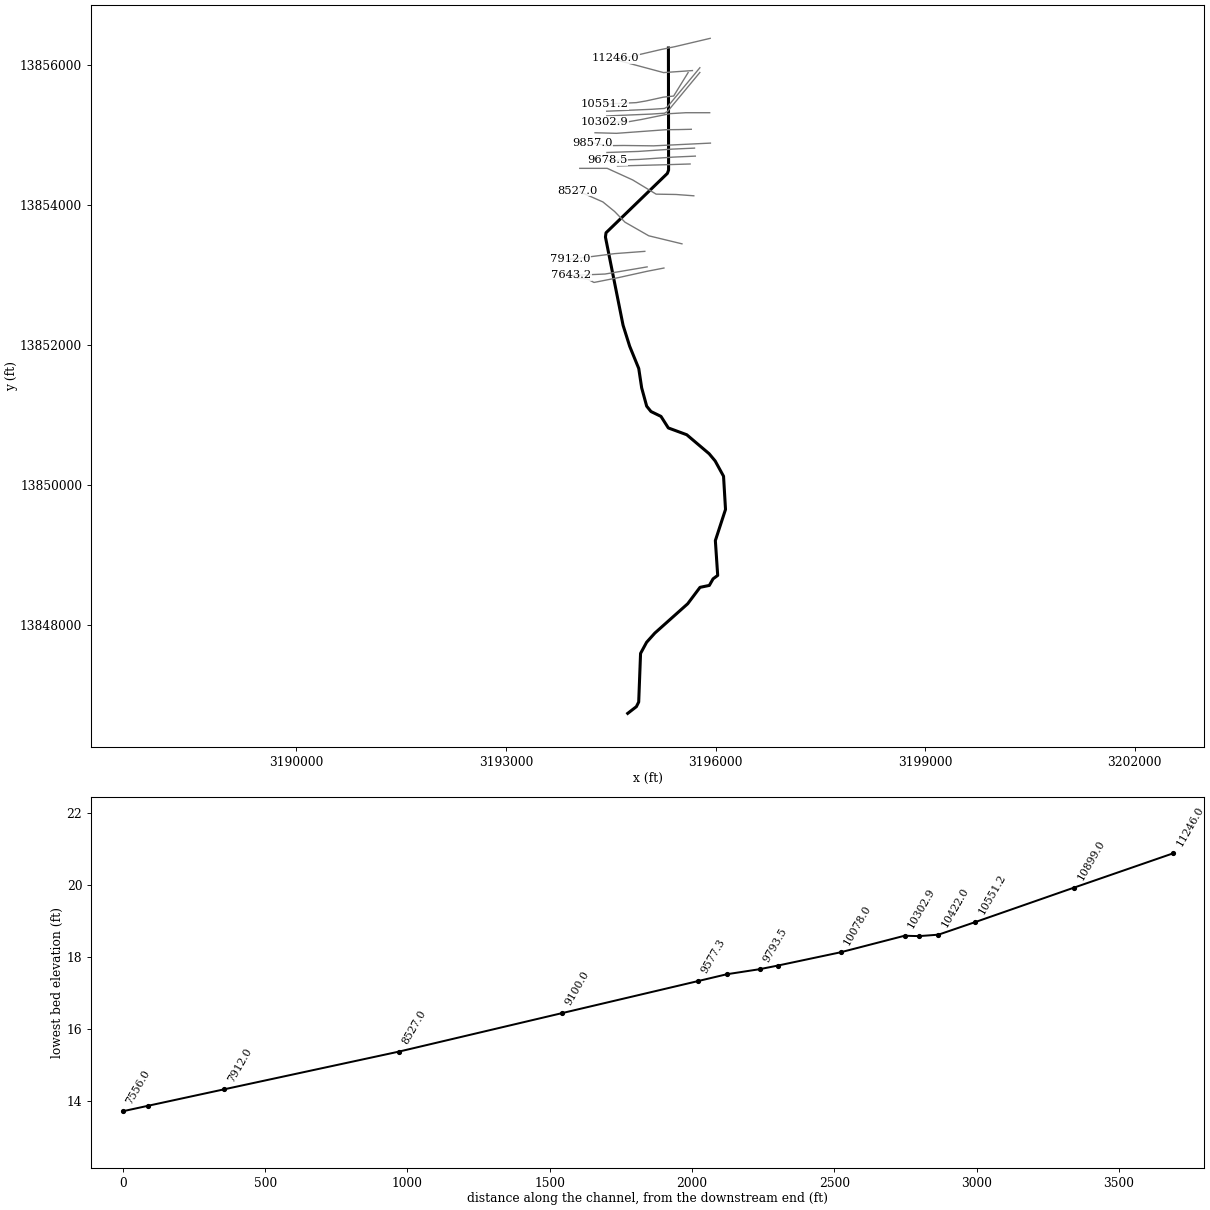
--- N104-00-00.PRJ (project) ---

Proj Title=N104-00-00
Current Plan=p02
Default Exp/Contr=.3,.1
English Units
Geom File=g01
Flow File=f01
Flow File=f02
Plan File=p01
Plan File=p02
Y Axis Title=Elevation
X Axis Title(PF)=Main Channel Distance
X Axis Title(XS)=Station
BEGIN DESCRIPTION:
Carpenters Bayou Watershed
Tributary 3.33 to Carpenters Bayou
HCFCD Unit N104-00-00
Flood Hazard Model
10, 2, 1, 0.2% Event
Filename N104-00-00.prj
Prepared by:  Watershed Concepts  Date: 07/11/02
Reviewed by:                      Date:
STATUS FINAL
END DESCRIPTION:
DSS Export Rating Curves= 0
DSS Export Rating Curve Sorted= 0
DSS Export Volume Flow Curves= 0
DXF OffsetX= 0
DXF OffsetY= 0
DXF ScaleX= 1
DXF ScaleY= 10

--- N104-00-00.p02 (plan) ---

Plan Title=Floodway
Version=Version 3.0.1  Mar 2001
Short Identifier=Floodway0607
Geom File=g01
Flow File=f02
Subcritical Flow
K Sum by GR= 0
Std Step Tol= 0.01
Critical Tol= 0.01
Num of Std Step Trials= 20
Max Error Tol= 0.3
Flow Tol Ratio= 0.001
Split Flow NTrial= 30
Split Flow Tol= 0.02
Split Flow Ratio= 0.02
Log Output Level= 0
Friction Slope Method= 1
Unsteady Friction Slope Method= 2
Parabolic Critical Depth
Global Vel Dist= 0 , 0 , 0
Global Log Level= 0
CheckData=True
Encroach Param=-1 ,0,0, 2
Encroach River=N104-00-00
Encroach Reach=Reach - 1
Encroach Node=11246.0
       1  4982.1 5052.45
Encroach Node=10899.0
       1 4981.35 5018.65
Encroach Node=10551.2
       1    4950    5050
Encroach Node=10422.0
       1 4960.78    5150
Encroach Node=10388.0
       1 4960.78    5150
Encroach Node=10354.0
       1 4960.78    5150
Encroach Node=10302.9
       1 4961.43    5130
Encroach Node=10078.0
       1    4977    5110
Encroach Node=9857.0
       1  4985.1    5100
Encroach Node=9793.5
       1  4985.1 5080.54
Encroach Node=9736.0
       1  4985.1 5080.54
Encroach Node=9678.5
       1  4985.1 5080.54
Encroach Node=9577.3
       1  4985.1 5023.78
Encroach Node=9100.0
       1 4978.95 5021.05
Encroach Node=8527.0
       1  4982.7  5024.8
Encroach Node=7912.0
       1    4940 5021.05
Encroach Node=7643.2
       1    4965    5060
Encroach Node=7556.0
       1 4935.46    5025
Encroach Node=7532.0
       1 4935.46    5025
Encroach Node=7508.0
       1 4935.46    5025
Encroach Node=7366.5
       1 4964.93  5020.7
Encroach Node=7213.0
       1  4979.3  5020.7
Encroach Node=6913.4
       1  4968.8  5048.4
Encroach Node=6833.2
       1  4968.8  5048.4
Encroach Node=6816.0
       1  4968.8  5048.4
Encroach Node=6798.8
       1  4968.8  5048.4
Encroach Node=6693.7
       1  4968.8  5048.4
Encroach Node=6516.0
       1  4970.6  5020.8
Encroach Node=6319.8
       1  4981.1  5021.3
Encroach Node=6253.0
       1 4933.47  5021.3
Encroach Node=6229.0
       1 4933.47  5021.3
Encroach Node=6205.0
       1 4933.47  5021.3
Encroach Node=6049.7
       1  4981.1  5021.3
Encroach Node=5787.0
       1  4979.9  5020.1
Encroach Node=5535.9
       1 4983.55 5029.53
Encroach Node=5401.0
       1 4983.55 5029.53
Encroach Node=5377.0
       1 4983.55 5029.53
Encroach Node=5353.0
       1 4983.55 5029.53
Encroach Node=5135.3
       1  4970.9 5029.53
Encroach Node=4799.0
       1  4979.7  5020.3
Encroach Node=4558.1
       1  4987.2  5036.3
Encroach Node=4513.5
       1  4944.3  4988.9
Encroach Node=4355.0
       1  4944.3  4988.9
Encroach Node=4196.5
       1  4944.3  4988.9
Encroach Node=4028.0
       1 4964.35 5033.75
Encroach Node=4017.0
       1 4964.35 5033.75
Encroach Node=4006.0
       1 4964.35 5033.75
Encroach Node=3998.6
       1 4964.35 5033.75
Encroach Node=3511.0
       1    4908  5033.2
Encroach Node=2876.0
       1    4942    5063
Encroach Node=2637.6
       1    4945    5070
Encroach Node=2598.1
       1    4905    5030
Encroach Node=2581.0
       1    4905    5030
Encroach Node=2563.9
       1    4905    5030
Encroach Node=2495.3
       1    4900    5100
Encroach Node=2310.4
       1    4750    5050
Encroach Node=2271.0
       1    4750    5050
Encroach Node=2231.6
       1    4750    5050
Encroach Node=2216.0
       1    4750    5050
Encroach Node=2150.7
       1    4750    5050
Encroach Node=2120.0
       1    4750    5050
Encroach Node=2089.3
       1    4750    5050
Encroach Node=2006.5
       1    4910    5105
Encroach Node=1562.0
       1    4975    5155
Encroach Node=936.0
       1    4933    5056
Encroach Reach=N104-00-00_0009
Encroach Node=11246.0
       1  4982.1 5052.45
Encroach Node=10899.0
       1 4981.35 5018.65
Encroach Node=10551.2
       1    4950    5050
Encroach Node=10422.0
       1 4960.78    5150
Encroach Node=10388.0
       1 4960.78    5150
Encroach Node=10354.0
       1 4960.78    5150
Encroach Node=10302.9
       1 4961.43    5130
Encroach Node=10078.0
       1    4977    5110
Encroach Node=9857.0
       1  4985.1    5100
Encroach Node=9793.5
       1  4985.1 5080.54
Encroach Node=9736.0
       1  4985.1 5080.54
Encroach Node=9678.5
       1  4985.1 5080.54
Encroach Node=9577.3
       1  4985.1 5023.78
Encroach Node=9100.0
       1 4978.95 5021.05
Encroach Node=8527.0
       1  4982.7  5024.8
Encroach Node=7912.0
       1    4940 5021.05
Encroach Node=7643.2
       1    4965    5060
Encroach Node=7556.0
       1 4935.46    5025
Encroach Node=7532.0
       1 4935.46    5025
Encroach Node=7508.0
       1 4935.46    5025
Encroach Node=7366.5
       1 4964.93  5020.7
Encroach Node=7213.0
       1  4979.3  5020.7
Encroach Node=6913.4
       1  4968.8  5048.4
Encroach Node=6833.2
       1  4968.8  5048.4
Encroach Node=6816.0
       1  4968.8  5048.4
Encroach Node=6798.8
       1  4968.8  5048.4
Encroach Node=6693.7
       1  4968.8  5048.4
Encroach Node=6516.0
       1  4970.6  5020.8
Encroach Node=6319.8
       1  4981.1  5021.3
Encroach Node=6253.0
       1 4933.47  5021.3
Encroach Node=6229.0
       1 4933.47  5021.3
Encroach Node=6205.0
       1 4933.47  5021.3
Encroach Node=6049.7
       1  4981.1  5021.3
Encroach Node=5787.0
       1  4979.9  5020.1
Encroach Node=5535.9
       1 4983.55 5029.53
Encroach Node=5401.0
       1 4983.55 5029.53
Encroach Node=5377.0
       1 4983.55 5029.53
Encroach Node=5353.0
       1 4983.55 5029.53
Encroach Node=5135.3
       1  4970.9 5029.53
Encroach Node=4799.0
       1  4979.7  5020.3
Encroach Node=4558.1
       1  4987.2  5036.3
Encroach Node=4513.5
       1  4944.3  4988.9
Encroach Node=4355.0
       1  4944.3  4988.9
Encroach Node=4196.5
       1  4944.3  4988.9
Encroach Node=4028.0
       1 4964.35 5033.75
Encroach Node=4017.0
       1 4964.35 5033.75
Encroach Node=4006.0
       1 4964.35 5033.75
Encroach Node=3998.6
       1 4964.35 5033.75
Encroach Node=3511.0
       1    4908  5033.2
Encroach Node=2876.0
       1    4942    5063
Encroach Node=2637.6
       1    4945    5070
Encroach Node=2598.1
       1    4905    5030
Encroach Node=2581.0
       1    4905    5030
Encroach Node=2563.9
       1    4905    5030
Encroach Node=2495.3
       1    4900    5100
Encroach Node=2310.4
       1    4750    5050
Encroach Node=2271.0
       1    4750    5050
Encroach Node=2231.6
       1    4750    5050
Encroach Node=2216.0
       1    4750    5050
Encroach Node=2150.7
       1    4750    5050
Encroach Node=2120.0
       1    4750    5050
Encroach Node=2089.3
       1    4750    5050
Encroach Node=2006.5
       1    4910    5105
Encroach Node=1562.0
       1    4975    5155
Encroach Node=936.0
       1    4933    5056
Computation Interval=1HOUR
Output Interval=1HOUR
Run HTab= 0
Run UNet= 0
Run PostProcess= 0
UNET Theta= 1
UNET ZTol= 0.02
UNET ZSATol= 0.1
UNET MxIter= 20
UNET MaxInSteps= 20
UNET DtIC= 0
UNET DtMin= 0
UNET MaxCRTS= 20
UNET WFStab= 2
UNET SFStab= 1
UNET WFX= 1
UNET SFX= 1
UNET Convert EG Bridges=-1
UNET Use Existing IB Tables=-1
Instantaneous Interval=1HOUR
DSS File=dss
Write IC File= 0
IC Time=0
Write Velocity= 0
Write Detailed= 0

--- N104-00-00.p01 (plan) ---

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Plan Title=FEMA Effective June 2007
Short Identifier=FEMAeff0607
Geom File=g01
Flow File=f01
Encroach Param=-1 ,0,0, 0

--- N104-00-00.f02 (steady flow) ---

Flow Title=Floodway
Program Version=3.13
Number of Profiles= 2
Profile Names=1PCT_100yr, 1PCTFloodway_100yrFW
River Rch & RM=N104-00-00,N104-00-00_0009    ,11246
     885     885
River Rch & RM=N104-00-00,N104-00-00_0009    ,9793.5
    1023    1023
River Rch & RM=N104-00-00,N104-00-00_0009    ,7556
    1162    1162
River Rch & RM=N104-00-00,N104-00-00_0009    ,6833.2
    1252    1252
River Rch & RM=N104-00-00,N104-00-00_0009    ,6253
    1334    1334
River Rch & RM=N104-00-00,N104-00-00_0009    ,5401
    1542    1542
River Rch & RM=N104-00-00,N104-00-00_0009    ,2598.1
    1915    1915
Boundary for River Rch & Prof#=N104-00-00,N104-00-00_0009    , 1
Up Type= 0
Dn Type= 3
Dn Slope=0.001
Boundary for River Rch & Prof#=N104-00-00,N104-00-00_0009    , 2
Up Type= 0
Dn Type= 3
Dn Slope=0.001
DSS Import GetInterval= 0
DSS Import GetPeak= 0
DSS Import FillOption= 0

--- N104-00-00.f01 (steady flow) ---

Flow Title=FEMA Effective June 2007
Number of Profiles= 4
Profile Names=10PCT_10yr, 2PCT_50yr, 1PCT_100yr, 0.2PCT_500yr
River Rch & RM=N104-00-00,N104-00-00_0009,11246
     499     753     885    1277
River Rch & RM=N104-00-00,N104-00-00_0009,9793.5
     577     870    1023    1476
River Rch & RM=N104-00-00,N104-00-00_0009,7556
     655     988    1162    1676
River Rch & RM=N104-00-00,N104-00-00_0009,6833.2
     705    1065    1252    1805
River Rch & RM=N104-00-00,N104-00-00_0009,6253
     752    1135    1334    1925
River Rch & RM=N104-00-00,N104-00-00_0009,5401
     869    1312    1542    2224
River Rch & RM=N104-00-00,N104-00-00_0009,2598.1
    1080    1629    1915    2763
Boundary for River Rch & Prof#=N104-00-00,N104-00-00_0009, 1
Up Type= 0
Dn Type= 3
Dn Slope= 0.00100
Boundary for River Rch & Prof#=N104-00-00,N104-00-00_0009, 2
Up Type= 0
Dn Type= 3
Dn Slope= 0.00100
Boundary for River Rch & Prof#=N104-00-00,N104-00-00_0009, 3
Up Type= 0
Dn Type= 3
Dn Slope= 0.00100
Boundary for River Rch & Prof#=N104-00-00,N104-00-00_0009, 4
Up Type= 0
Dn Type= 3
Dn Slope= 0.00100

--- N104-00-00.g01 (geometry) ---

Geom Title=N104-00-00 June 2007

River Reach=N104-00-00,N104-00-00_0009
Reach XY= 30
      3195324.60     13856249.64         3195327        13854504
      3195309.25        13854456      3194431.25        13853607
         3194423        13853546      3194675.25        13852285
         3194770        13851984      3194899.75     13851666.42
      3194941.75        13851389       3195013.5        13851127
      3195074.75        13851051      3195218.25        13850981
      3195323.25        13850816      3195587.07      13850718.8
      3195907.75        13850447      3195993.75        13850344
      3196113.71     13850125.54         3196142     13849650.96
       3195996.5        13849205         3196030        13848707
      3195963.75        13848658      3195910.28     13848563.99
      3195776.83     13848536.29      3195600.44     13848301.49
      3195129.95     13847882.04       3195012.5        13847751
      3194925.78     13847591.32      3194899.15     13846896.68
      3194865.86      13846830.1      3194741.75        13846734

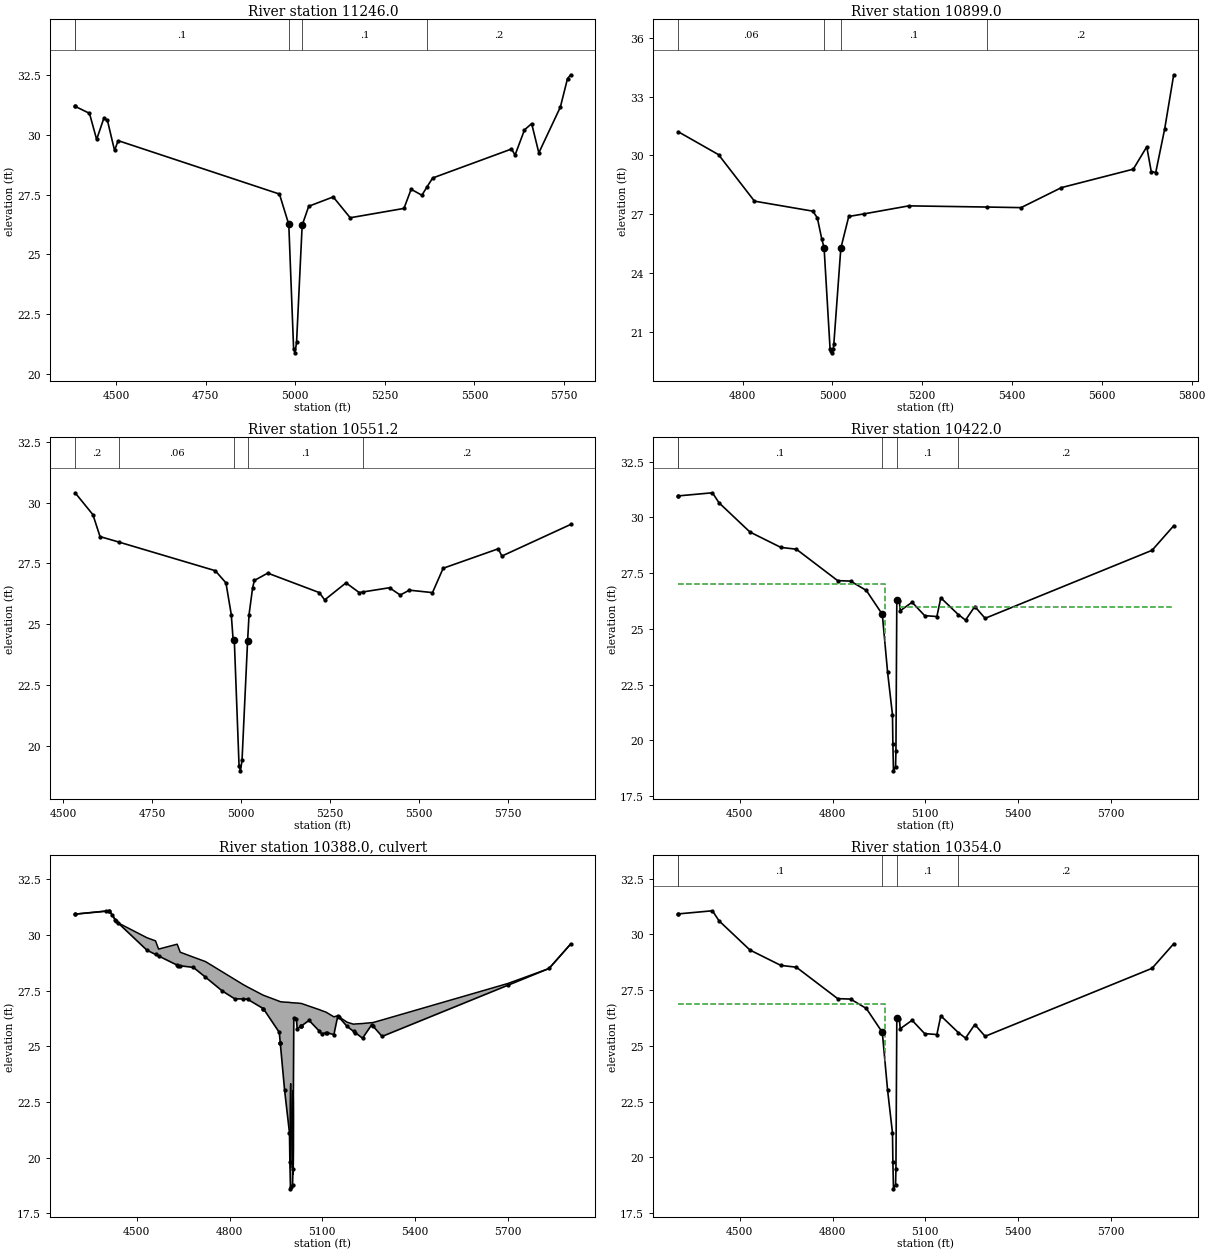
Type RM Length L Ch R = 1 ,11246.0,377.4,347,280.9
XS GIS Cut Line= 5
      3195922.78     13856387.90      3195416.64     13856268.62
      3195213.54     13856226.71      3194700.96     13856107.43
      3194572.01     13856104.21
BEGIN DESCRIPTION:
Cross Section 11246
Located At: 1ST XS US WOODFOREST
END DESCRIPTION:
#Sta/Elev= 30
    4386   31.18  4386.2   31.18    4426   30.89    4446    29.8    4466   30.68
    4476    30.6    4496   29.34    4506   29.75    4956   27.52  4982.1   26.25
  4995.5   21.07  4999.4   20.89  5003.8   21.33  5019.4   26.22  5037.7   27.01
    5106    27.4  5153.4   26.53  5303.4   26.92  5323.4   27.72  5353.4   27.47
  5368.2   27.83  5383.4   28.19  5603.4    29.4  5613.4   29.15  5639.7    30.2
  5659.7   30.46  5679.7   29.24  5739.7   31.15  5759.7   32.34  5768.6    32.5
#Mann= 5 , 1 , 0
 4386.00     0.2       0  4386.2     0.1       0  4982.1    0.04       0
  5019.4     0.1       0  5368.2     0.2       0
Bank Sta=4982.10,5019.40
Exp/Cntr=0.3,0.1

Type RM Length L Ch R = 1 ,10899.0,347.1,347.8,408
XS GIS Cut Line= 3
      3195668.10     13855926.90      3195255.45     13855897.89
      3194588.88     13856076.49
BEGIN DESCRIPTION:
Cross Section 10899 - Interpolated
END DESCRIPTION:
#Sta/Elev= 25
  4656.3   31.21  4746.3   30.04  4826.3   27.67  4956.3   27.16  4966.3   26.82
  4976.3   25.73 4981.35    25.3 4994.75   20.12 4996.75   20.05 4998.65   19.94
 5001.75   20.16 5003.05   20.38 5018.65   25.27  5036.3   26.89    5070   27.02
    5170   27.43  5344.1   27.37    5420   27.34    5510   28.36    5670    29.3
    5700   30.44    5710   29.18    5720   29.13    5740   31.36    5760   34.11
#Mann= 4 , 1 , 0
 4656.30    0.06       0 4981.35    0.04       0 5018.65     0.1       0
  5344.1     0.2       0
Bank Sta=4981.35,5018.65
Exp/Cntr=0.3,0.1

Type RM Length L Ch R = 1 ,10551.2,69.9,129.2,154
XS GIS Cut Line= 6
      3195606.33     13855897.77      3195399.45     13855562.57
      3195252.80     13855546.86      3195001.40     13855491.87
      3194862.61     13855468.30      3194409.57     13855447.35
BEGIN DESCRIPTION:
Cross Section 10551.2 - Interpolated
END DESCRIPTION:
#Sta/Elev= 30
  4533.9    30.4  4583.9    29.5  4603.9    28.6    4656   28.38  4927.8    27.2
  4957.8    26.7  4972.8    25.4  4977.8    24.4 4981.35   24.34 4994.75   19.16
 4998.65   18.98 5003.05   19.42 5018.65   24.31  5022.8    25.4  5032.8    26.5
  5037.8    26.8  5075.3    27.1  5220.3    26.3  5235.3      26  5295.3    26.7
  5332.6    26.3  5344.1   26.33  5417.6    26.5  5447.6    26.2  5473.4    26.4
  5538.4    26.3  5568.4    27.3  5723.4    28.1  5733.4    27.8  5926.9    29.1
#Mann= 5 , 1 , 0
 4533.90     0.2       0    4656    0.06       0 4981.35    0.04       0
 5018.65     0.1       0  5344.1     0.2       0
Bank Sta=4981.35,5018.65
Exp/Cntr=0.5,0.3

Type RM Length L Ch R = 1 ,10422.0,68,68,68
XS GIS Cut Line= 5
      3195774.70     13855967.35      3195311.96     13855410.02
      3195268.63     13855385.26      3195080.88     13855372.88
      3194441.06     13855345.72
BEGIN DESCRIPTION:
Upstream Section of Bridge/Culvert/Weir
END DESCRIPTION:
#Sta/Elev= 30
  4300.4   30.96  4300.8   30.96  4411.4    31.1  4432.7   30.65  4532.7   29.34
  4632.7   28.65  4682.7   28.57 4816.47   27.16 4858.06   27.14  4909.1   26.72
 4960.78   25.65 4977.94   23.05 4993.72   21.14 4995.02   19.84 4996.94   18.63
 5003.75   18.82  5004.9   19.53 5007.74    26.3 5015.93   26.26 5018.77   25.81
 5057.14   26.19 5097.82   25.59 5137.34   25.55    5150   26.39  5206.5   25.64
    5230   25.39    5260      26  5293.3   25.47  5833.3   28.52  5903.3   29.62
#Mann= 5 , 1 , 0
 4300.40     0.2       0  4300.8     0.1       0 4960.78   0.042       0
 5007.74     0.1       0  5206.5     0.2       0
#XS Ineff= 2 , 0
       0    4970      27    5018       0      26
Bank Sta=4960.78,5007.74
Exp/Cntr=0.5,0.3

Type RM Length L Ch R = 2 ,10388.0,,,
BEGIN DESCRIPTION:
ELGIN ROAD,  SKEW ANGLE OF 40 DEGREES
Structure ID: N04-13
END DESCRIPTION:
Bridge Culvert--1,0,-1,-1, 0
Deck Dist Width WeirC Skew NumUp NumDn MinLoCord MaxHiCord MaxSubmerge Is_Ogee
10,48,3,,58,58,,,0.95,0,1,1,,
  4300.4  4300.8  4400.4  4410.4  4411.4  4420.4  4430.4  4432.7  4440.4  4532.7
  4560.4  4570.4  4630.4  4632.7  4640.4  4682.7    4722  4776.4 4816.47  4844.9
 4858.06 4908.92  4909.1 4960.78 4963.79  4963.9 4964.01 4977.94 4993.72 4995.02
 4996.94 4998.16 5003.75  5004.9 5007.74 5015.93 5018.77 5031.99  5032.1 5032.21
 5057.14  5090.7 5097.82  5112.2 5114.44 5137.34    5150  5152.7    5180  5200.8
  5206.5    5230    5260  5262.9  5293.3  5700.7  5833.3  5903.3
   30.93   30.93   31.07   31.08   31.08   30.89   30.68   30.63   30.53   29.87
   29.73   29.36   29.58    29.5   29.22      29    28.8   28.34      28   27.76
   27.66   27.29   27.29   27.02      27      27      27   26.98   26.97   26.96
   26.96   26.96   26.95   26.95   26.95   26.94   26.94   26.92   26.92   26.92
    26.8   26.64    26.6   26.53   26.51   26.32   26.37   26.33   26.08   25.99
      26   26.02   26.06   26.06   26.18   27.82   28.49   29.59
   30.93   30.93   31.06   31.07   31.07   30.88   30.67   30.62   30.52   29.31
   29.12   29.05   28.64   28.62   28.61   28.54    28.1   27.48   27.13   27.12
   27.11   26.69   26.69   25.62   25.16   25.15   25.13   23.02   21.11   19.81
    18.6   18.68   18.79    19.5   26.27   26.23   25.78   25.91   25.91   25.91
   26.16   25.67   25.56    25.6   25.61   25.52   26.36   26.32   25.89   25.67
   25.61   25.36   25.97   25.92   25.44   27.74   28.49   29.59
  4300.4  4300.8  4400.4  4410.4  4411.4  4420.4  4430.4  4432.7  4440.4  4532.7
  4560.4  4570.4  4630.4  4632.7  4640.4  4682.7    4722  4776.4 4816.47  4844.9
 4858.06 4908.92  4909.1 4960.78 4963.79  4963.9 4964.01 4977.94 4993.72 4995.02
 4996.94 4998.16 5003.75  5004.9 5007.74 5015.93 5018.77 5031.99  5032.1 5032.21
 5057.14  5090.7 5097.82  5112.2 5114.44 5137.34    5150  5152.7    5180  5200.8
  5206.5    5230    5260  5262.9  5293.3  5700.7  5833.3  5903.3
   30.94   30.94   31.07   31.08   31.08   30.89   30.68   30.63   30.53   29.87
   29.73   29.36   29.58    29.5   29.22      29    28.8   28.34      28   27.76
   27.66   27.29   27.29   27.02      27      27      27   26.98   26.97   26.96
   26.96   26.96   26.95   26.95   26.95   26.94   26.94   26.92   26.92   26.92
    26.8   26.64    26.6   26.53   26.51   26.32   26.37   26.33   26.08   25.99
      26   26.02   26.06   26.06   26.18   27.82    28.5    29.6
   30.94   30.94   31.07   31.08   31.08   30.89   30.68   30.63   30.53   29.32
   29.13   29.06   28.65   28.63   28.62   28.55   28.11   27.49   27.14   27.13
   27.12    26.7    26.7   25.63   25.17   25.16   25.14   23.03   21.12   19.82
   18.61   18.69    18.8   19.51   26.28   26.24   25.79   25.92   25.92   25.92
   26.17   25.68   25.57   25.61   25.62   25.53   26.37   26.33    25.9   25.68
   25.62   25.37   25.98   25.93   25.45   27.75    28.5    29.6
BR Coef= 1 , 0 , 0 ,1.25, 0 ,,,0.8,-1,2,0,
Wspro=,,,, 1 ,,,, 0 ,,,, 0 ,,,,-1 ,-1 ,-1 , 0 , 0 , 0 , 0 , 0
Culvert=1,3.8,,48.0,0.015,0.2,1.0,1,3,19.53,4997.60,19.19,4997.60,Culvert #1  ,0,10
Culvert=1,3.8,,48.0,0.015,0.2,1.0,1,3,19.23,5005.20,18.91,5005.20,Culvert #2  ,0,10
BC Design=,, 0 ,, 0 ,,,,,,
BR U #Sta/Elev= 58
  4300.4   30.93  4300.8   30.93  4400.4   31.06  4410.4   31.07  4411.4   31.07
  4420.4   30.88  4430.4   30.67  4432.7   30.62  4440.4   30.52  4532.7   29.31
  4560.4   29.12  4570.4   29.05  4630.4   28.64  4632.7   28.62  4640.4   28.61
  4682.7   28.54    4722    28.1  4776.4   27.48 4816.47   27.13  4844.9   27.12
 4858.06   27.11 4908.92   26.69  4909.1   26.69 4960.78   25.62 4963.79   25.16
  4963.9   25.15 4964.01   25.13 4977.94   23.02 4993.72   21.11 4995.02   19.81
 4996.94    18.6 4998.16   18.68 5003.75   18.79  5004.9    19.5 5007.74   26.27
 5015.93   26.23 5018.77   25.78 5031.99   25.91  5032.1   25.91 5032.21   25.91
 5057.14   26.16  5090.7   25.67 5097.82   25.56  5112.2    25.6 5114.44   25.61
 5137.34   25.52    5150   26.36  5152.7   26.32    5180   25.89  5200.8   25.67
  5206.5   25.61    5230   25.36    5260   25.97  5262.9   25.92  5293.3   25.44
  5700.7   27.74  5833.3   28.49  5903.3   29.59
BR U #Mann= 5
 4300.40     0.2  4300.8     0.1 4960.78   0.042 5007.74     0.1  5206.5     0.2
BR U Banks=4960.78,5007.74
BR D #Sta/Elev= 58
  4300.4   30.94  4300.8   30.94  4400.4   31.07  4410.4   31.08  4411.4   31.08
  4420.4   30.89  4430.4   30.68  4432.7   30.63  4440.4   30.53  4532.7   29.32
  4560.4   29.13  4570.4   29.06  4630.4   28.65  4632.7   28.63  4640.4   28.62
  4682.7   28.55    4722   28.11  4776.4   27.49 4816.47   27.14  4844.9   27.13
 4858.06   27.12 4908.92    26.7  4909.1    26.7 4960.78   25.63 4963.79   25.17
  4963.9   25.16 4964.01   25.14 4977.94   23.03 4993.72   21.12 4995.02   19.82
 4996.94   18.61 4998.16   18.69 5003.75    18.8  5004.9   19.51 5007.74   26.28
 5015.93   26.24 5018.77   25.79 5031.99   25.92  5032.1   25.92 5032.21   25.92
 5057.14   26.17  5090.7   25.68 5097.82   25.57  5112.2   25.61 5114.44   25.62
 5137.34   25.53    5150   26.37  5152.7   26.33    5180    25.9  5200.8   25.68
  5206.5   25.62    5230   25.37    5260   25.98  5262.9   25.93  5293.3   25.45
  5700.7   27.75  5833.3    28.5  5903.3    29.6
BR D #Mann= 5
 4300.40     0.2  4300.8     0.1 4960.78   0.042 5007.74     0.1  5206.5     0.2
BR D Banks=4960.78,5007.74

Type RM Length L Ch R = 1 ,10354.0,51.1,51.1,51.1
XS GIS Cut Line= 5
      3195774.26     13855899.35      3195311.52     13855342.02
      3195268.19     13855317.26      3195080.44     13855304.88
      3194440.62     13855277.72
BEGIN DESCRIPTION:
Downstream Section of Bridge/Culvert/Weir
END DESCRIPTION:
#Sta/Elev= 30
  4300.4   30.92  4300.8   30.92  4411.4   31.06  4432.7   30.61  4532.7    29.3
  4632.7   28.61  4682.7   28.53 4816.47   27.12 4858.06    27.1  4909.1   26.68
 4960.78   25.61 4977.94   23.01 4993.72    21.1 4995.02    19.8 4996.94   18.59
 5003.75   18.78  5004.9   19.49 5007.74   26.26 5015.93   26.22 5018.77   25.77
 5057.14   26.15 5097.82   25.55 5137.34   25.51    5150   26.35  5206.5    25.6
    5230   25.35    5260   25.96  5293.3   25.43  5833.3   28.48  5903.3   29.58
#Mann= 5 , 1 , 0
 4300.40     0.2       0  4300.8     0.1       0 4960.78   0.042       0
 5007.74     0.1       0  5206.5     0.2       0
#XS Ineff= 2 , 0
       0    4970    26.9    5018       0    25.8
Bank Sta=4960.78,5007.74
Exp/Cntr=0.5,0.3

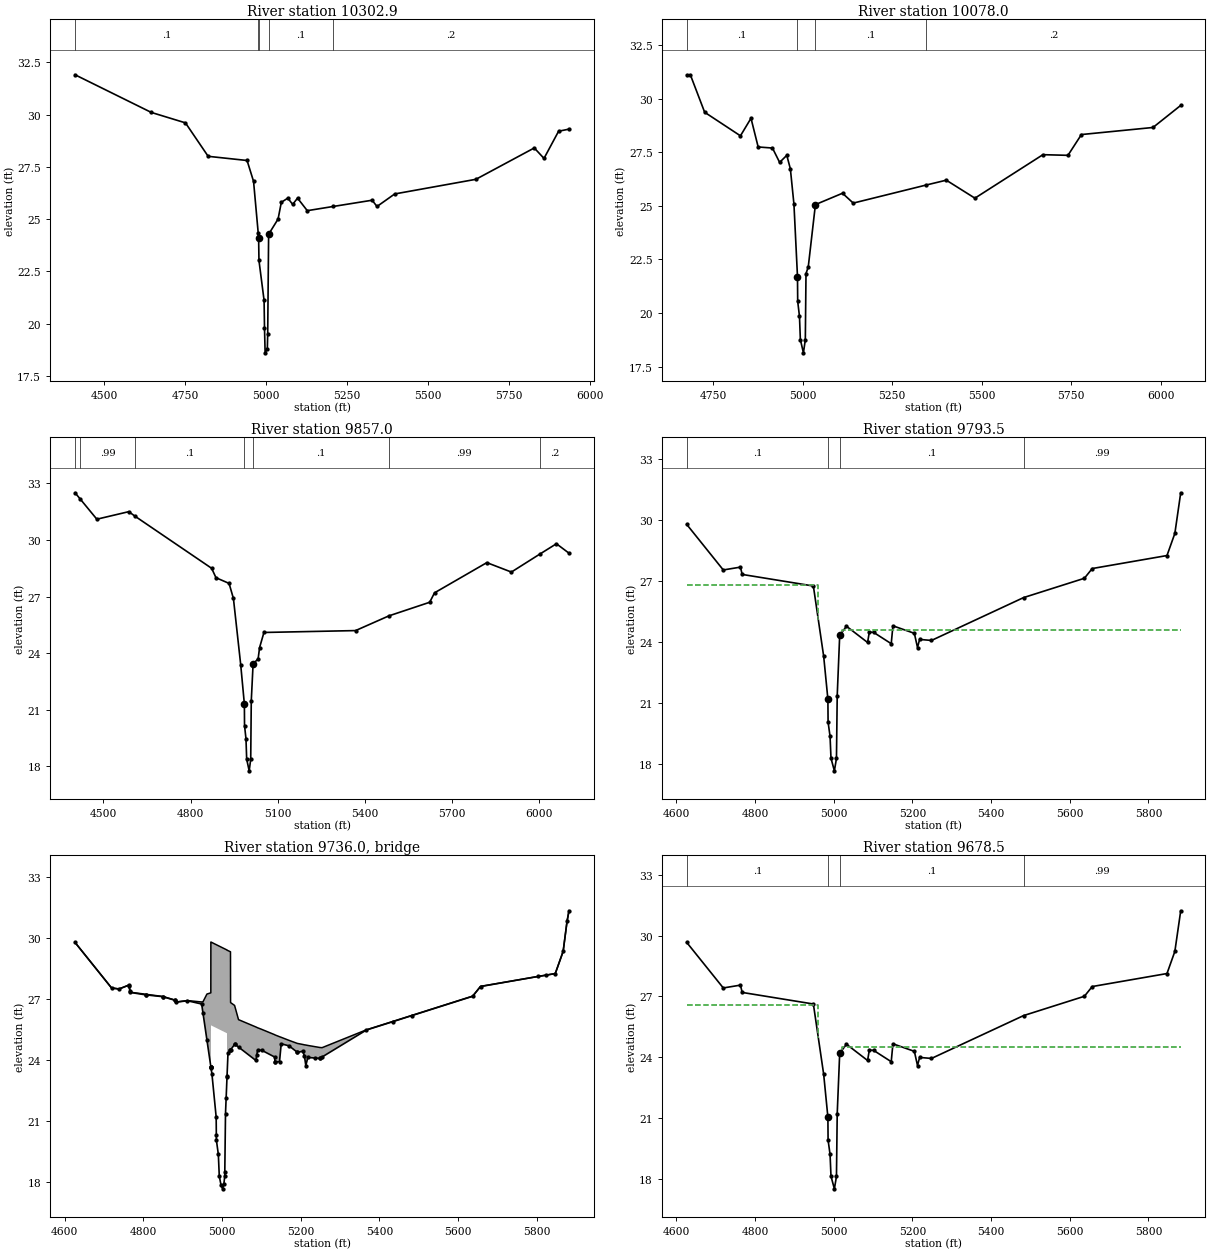
Type RM Length L Ch R = 1 ,10302.9,231,224.9,196
XS GIS Cut Line= 6
      3195915.34     13855324.27      3195574.91     13855324.27
      3195349.69     13855311.17      3194938.55     13855227.38
      3194726.44     13855190.71      3194404.33     13855190.71
BEGIN DESCRIPTION:
Cross Section 10302.9 - Interpolated
END DESCRIPTION:
#Sta/Elev= 30
  4410.9    31.9  4645.9    30.1  4751.3    29.6  4821.3      28  4941.3    27.8
  4961.3    26.8  4975.7   24.32  4976.9    24.1 4977.94   23.02 4993.72   21.11
 4995.02   19.81 4996.94    18.6 5003.75   18.79  5004.9    19.5 5007.74   24.27
  5036.9      25  5046.9    25.8  5066.9      26  5081.9    25.7  5096.9      26
  5126.9    25.4  5206.5    25.6  5326.9    25.9  5341.9    25.6  5396.5    26.2
  5646.8    26.9  5826.8    28.4  5856.8    27.9  5901.8    29.2  5933.9    29.3
#Mann= 5 , 1 , 0
 4410.90     0.1       0  4975.7     0.1       0  4976.9    0.04       0
 5007.74     0.1       0  5206.5     0.2       0
Bank Sta=4976.90,5007.74
Exp/Cntr=0.3,0.1

Type RM Length L Ch R = 1 ,10078.0,218.3,221,219
XS GIS Cut Line= 5
      3195652.17     13855087.17      3195472.67     13855083.04
      3195286.98     13855080.98      3194581.36     13855029.40
      3194273.94     13855037.65
BEGIN DESCRIPTION:
Cross Section 10078 - Interpolated
END DESCRIPTION:
#Sta/Elev= 30
  4675.8   31.11  4685.8   31.12  4725.8   29.37  4825.8   28.27  4855.3   29.09
  4875.3   27.75  4915.3    27.7  4935.3   27.03  4955.3   27.36  4965.3   26.73
  4975.3   25.08  4985.2    21.7  4985.8   20.54  4990.8   19.84  4993.2   18.76
  5001.8   18.14  5007.1   18.75    5009   21.84  5015.3   22.15  5035.3   25.06
    5111   25.59    5141   25.13    5344   25.97    5401    26.2    5481   25.36
    5671   27.39    5741   27.36  5778.6   28.33  5978.6   28.66  6056.1   29.69
#Mann= 4 , 1 , 0
 4675.80     0.1       0  4985.2    0.04       0  5035.3     0.1       0
    5344     0.2       0
Bank Sta=4985.20,5035.30
Exp/Cntr=0.3,0.1

Type RM Length L Ch R = 1 ,9857.0,62.9,63.5,61.8
XS GIS Cut Line= 5
      3195925.82     13854889.56      3195111.39     13854850.28
      3194689.77     13854855.52      3194425.28     13854852.90
      3194231.50     13854894.80
BEGIN DESCRIPTION:
Cross Section 9857.0 - Interpolated
END DESCRIPTION:
#Sta/Elev= 30
  4402.4    32.5  4419.6   32.18  4477.4    31.1  4587.4    31.5  4608.6   31.26
  4872.4    28.5  4887.4      28  4932.4    27.7  4947.4    26.9  4972.4    23.4
  4985.1    21.3  4985.6   20.17  4990.6   19.47    4993   18.39  5001.6   17.77
  5006.9   18.38  5008.8   21.47  5015.1   23.44  5032.4    23.7  5037.4    24.3
  5052.4    25.1  5367.8    25.2  5482.5   25.98  5622.8    26.7  5639.4    27.2
  5819.4    28.8  5903.9    28.3  6001.6   29.25  6058.9    29.8  6102.2    29.3
#Mann= 7 , 1 , 0
 4402.40     0.2       0  4419.6    0.99       0  4608.6     0.1       0
  4985.1    0.04       0  5015.1     0.1       0  5482.5    0.99       0
  6001.6     0.2       0
Bank Sta=4985.10,5015.10
Exp/Cntr=0.5,0.3

Type RM Length L Ch R = 1 ,9793.5,115,115,115
XS GIS Cut Line= 4
      3195698.22     13854817.88      3195379.44     13854803.52
      3194892.07     13854770.39      3194444.41     13854755.48
BEGIN DESCRIPTION:
Upstream Section of Bridge/Culvert/Weir
END DESCRIPTION:
#Sta/Elev= 30
  4626.4    29.8  4719.2   27.56  4762.9    27.7  4767.2   27.34  4948.2   26.77
  4974.4   23.31  4985.1    21.2  4985.6   20.07  4990.6   19.37    4993   18.29
  5001.6   17.67  5006.9   18.28  5008.8   21.37  5015.1   24.34  5032.3   24.79
    5086   23.99  5090.4    24.5  5101.1   24.49  5146.1   23.93  5150.4   24.81
  5204.9   24.44  5212.9   23.74  5218.2   24.14  5248.4   24.09  5482.5    26.2
    5637   27.15    5657   27.63    5847   28.27    5867   29.36  5881.9   31.36
#Mann= 4 , 1 , 0
 4626.40     0.1       0  4985.1    0.04       0  5015.1     0.1       0
  5482.5    0.99       0
#XS Ineff= 2 , 0
       0    4961    26.8    5022       0    24.6
Bank Sta=4985.10,5015.10
Exp/Cntr=0.5,0.3

Type RM Length L Ch R = 3 ,9736.0,,,
BEGIN DESCRIPTION:
WOODFOREST DRIVE
Structure ID: N04-12
END DESCRIPTION:
Bridge Culvert--1,0,-1,-1, 0
Deck Dist Width WeirC Skew NumUp NumDn MinLoCord MaxHiCord MaxSubmerge Is_Ogee
10,95,2.6,, 45, 45,,,0.95,0,1,1,,
  4626.4  4719.2  4738.3  4762.9  4767.2  4849.9  4881.2  4882.7  4912.1  4948.2
  4951.6  4961.6 4971.49  4971.6 4971.81  4971.9 5012.59  5012.7  5015.1  5021.5
 5021.71  5031.9  5041.9    5086  5090.4  5101.1  5133.7  5134.4  5146.1  5150.4
  5170.3  5191.4  5204.9  5209.3  5212.9  5218.2  5248.4  5254.2    5367    5637
    5657    5847    5867    5877  5881.9
   29.78   27.54   27.49   27.68   27.33   27.12   26.94   26.85   26.92   26.85
   26.86   27.24    27.3    29.8    29.8    29.8   29.41    29.4   29.38   29.32
   26.82   26.68   25.98   25.62   25.58    25.5   25.24   25.23   25.14   25.11
   24.96   24.81   24.76   24.74   24.73   24.71   24.61    24.6   25.48   27.14
   27.62   28.25   29.34   30.83   31.34
   29.78   27.54   27.49   27.68   27.32   27.11   26.93   26.84   26.91   26.75
    26.3   24.98   23.67   23.66   23.63    25.7   25.31   23.19   24.32   24.49
   24.49   24.76   24.63   23.97   24.48   24.47   24.14    23.9   23.91   24.79
   24.69   24.37   24.42   24.21   23.72   24.12   24.07   24.14   25.47   27.13
   27.61   28.25   29.34   30.83   31.34
  4626.4  4719.2  4738.3  4762.9  4767.2  4849.9  4881.2  4882.7  4912.1  4948.2
  4951.6  4961.6 4971.49  4971.6 4971.81  4971.9 5012.59  5012.7  5015.1  5021.5
 5021.71  5031.9  5041.9    5086  5090.4  5101.1  5133.7  5134.4  5146.1  5150.4
  5170.3  5191.4  5204.9  5209.3  5212.9  5218.2  5248.4  5254.2    5367    5637
    5657    5847    5867    5877  5881.9
   29.78   27.54   27.49   27.68   27.33   27.12   26.94   26.85   26.92   26.85
   26.86   27.24    27.3    29.8    29.8    29.8   29.41    29.4   29.38   29.32
   26.82   26.68   25.98   25.62   25.58    25.5   25.24   25.23   25.14   25.11
   24.96   24.81   24.76   24.74   24.73   24.71   24.61    24.6   25.48   27.14
   27.62   28.25   29.34   30.83   31.34
   29.68   27.44   27.39   27.58   27.22   27.01   26.83   26.74   26.81   26.65
    26.2   24.88   23.57   23.56   23.53    25.6   25.21   23.09   24.22   24.39
   24.39   24.66   24.53   23.87   24.38   24.37   24.04    23.8   23.81   24.69
   24.59   24.27   24.32   24.11   23.62   24.02   23.97   24.04   25.37   27.03
   27.51   28.15   29.24   30.73   31.24
Abutment Skew #Up #Dn=, 2 , 2
 4971.70 4985.60
   25.70   20.05
 4971.70 4985.60
   25.60   19.95
Abutment Skew #Up #Dn=, 2 , 2
 5010.40 5012.79
   22.10   25.31
 5010.40 5012.79
   22.00   25.21
BR Coef= 1 , 1 , 0 ,1.25, 0 ,,,0.8,0,2,0,
Wspro=,,,, 1 ,,,, 0 ,,,, 0 ,,,,-1 ,-1 ,-1 , 0 , 0 , 0 , 0 , 0
BC Design=,, 0 ,, 0 ,,,,,,
BR U #Sta/Elev= 76
  4626.4   29.78  4719.2   27.54  4738.3   27.49  4762.9   27.68  4763.4   27.63
  4765.8   27.41  4767.2   27.32  4806.1    27.2  4806.2    27.2  4849.9   27.11
  4851.2    27.1  4881.1   26.93  4881.2   26.93  4882.7   26.84  4912.1   26.91
  4948.2   26.75  4951.6    26.3  4961.6   24.98 4971.49   23.67  4971.6   23.66
 4971.71   23.65 4971.81   23.63  4971.9   23.62  4974.4   23.29  4985.1   21.18
  4985.5   20.28  4985.6   20.05  4990.6   19.35    4993   18.27  4997.5   17.83
  5001.6   17.65  5004.6   17.89  5006.9   18.26    5007   18.46  5008.8   21.35
  5010.4    22.1 5012.59   23.14  5012.7   23.19  5015.1   24.32 5021.39   24.48
  5021.5   24.49 5021.71   24.49  5031.9   24.76  5032.3   24.77  5041.9   24.63
    5086   23.97  5088.2   24.22  5090.4   24.48  5101.1   24.47  5133.7   24.14
  5134.4    23.9  5134.6    23.9  5146.1   23.91  5150.4   24.79  5170.3   24.69
  5190.9   24.38  5191.4   24.37  5204.9   24.42  5209.3   24.21  5212.9   23.72
  5218.2   24.12    5236   24.09  5248.3   24.07  5248.4   24.07  5254.2   24.14
    5367   25.47    5434   25.88  5482.5   26.18    5637   27.13    5657   27.61
    5804   28.11    5824   28.17    5847   28.25    5867   29.34    5877   30.83
  5881.9   31.34
BR U #Mann= 4
 4626.40     0.1  4985.1    0.04  5015.1     0.1  5482.5    0.99
BR U Banks=4985.10,5015.10
BR D #Sta/Elev= 76
  4626.4   29.68  4719.2   27.44  4738.3   27.39  4762.9   27.58  4763.4   27.53
  4765.8   27.31  4767.2   27.22  4806.1    27.1  4806.2    27.1  4849.9   27.01
  4851.2      27  4881.1   26.83  4881.2   26.83  4882.7   26.74  4912.1   26.81
  4948.2   26.65  4951.6    26.2  4961.6   24.88 4971.49   23.57  4971.6   23.56
 4971.71   23.55 4971.81   23.53  4971.9   23.52  4974.4   23.19  4985.1   21.08
  4985.5   20.18  4985.6   19.95  4990.6   19.25    4993   18.17  4997.5   17.73
  5001.6   17.55  5004.6   17.79  5006.9   18.16    5007   18.36  5008.8   21.25
  5010.4      22 5012.59   23.04  5012.7   23.09  5015.1   24.22 5021.39   24.38
  5021.5   24.39 5021.71   24.39  5031.9   24.66  5032.3   24.67  5041.9   24.53
    5086   23.87  5088.2   24.12  5090.4   24.38  5101.1   24.37  5133.7   24.04
  5134.4    23.8  5134.6    23.8  5146.1   23.81  5150.4   24.69  5170.3   24.59
  5190.9   24.28  5191.4   24.27  5204.9   24.32  5209.3   24.11  5212.9   23.62
  5218.2   24.02    5236   23.99  5248.3   23.97  5248.4   23.97  5254.2   24.04
    5367   25.37    5434   25.78  5482.5   26.08    5637   27.03    5657   27.51
    5804   28.01    5824   28.07    5847   28.15    5867   29.24    5877   30.73
  5881.9   31.24
BR D #Mann= 4
 4626.40     0.1  4985.1    0.04  5015.1     0.1  5482.5    0.99
BR D Banks=4985.10,5015.10

Type RM Length L Ch R = 1 ,9678.5,101.2,101.2,101.2
XS GIS Cut Line= 4
      3195709.66     13854703.46      3195390.88     13854689.10
      3194903.51     13854655.97      3194455.86     13854641.05
BEGIN DESCRIPTION:
Downstream Section of Bridge/Culvert/Weir
END DESCRIPTION:
#Sta/Elev= 30
  4626.4   29.66  4719.2   27.42  4762.9   27.56  4767.2    27.2  4948.2   26.63
  4974.4   23.17  4985.1   21.06  4985.6   19.93  4990.6   19.23    4993   18.15
  5001.6   17.53  5006.9   18.14  5008.8   21.23  5015.1    24.2  5032.3   24.65
    5086   23.85  5090.4   24.36  5101.1   24.35  5146.1   23.79  5150.4   24.67
  5204.9    24.3  5212.9    23.6  5218.2      24  5248.4   23.95  5482.5   26.06
    5637   27.01    5657   27.49    5847   28.13    5867   29.22  5881.9   31.22
#Mann= 4 , 1 , 0
 4626.40     0.1       0  4985.1    0.04       0  5015.1     0.1       0
  5482.5    0.99       0
#XS Ineff= 2 , 0
       0    4961    26.6    5022       0    24.5
Bank Sta=4985.10,5015.10
Exp/Cntr=0.5,0.3

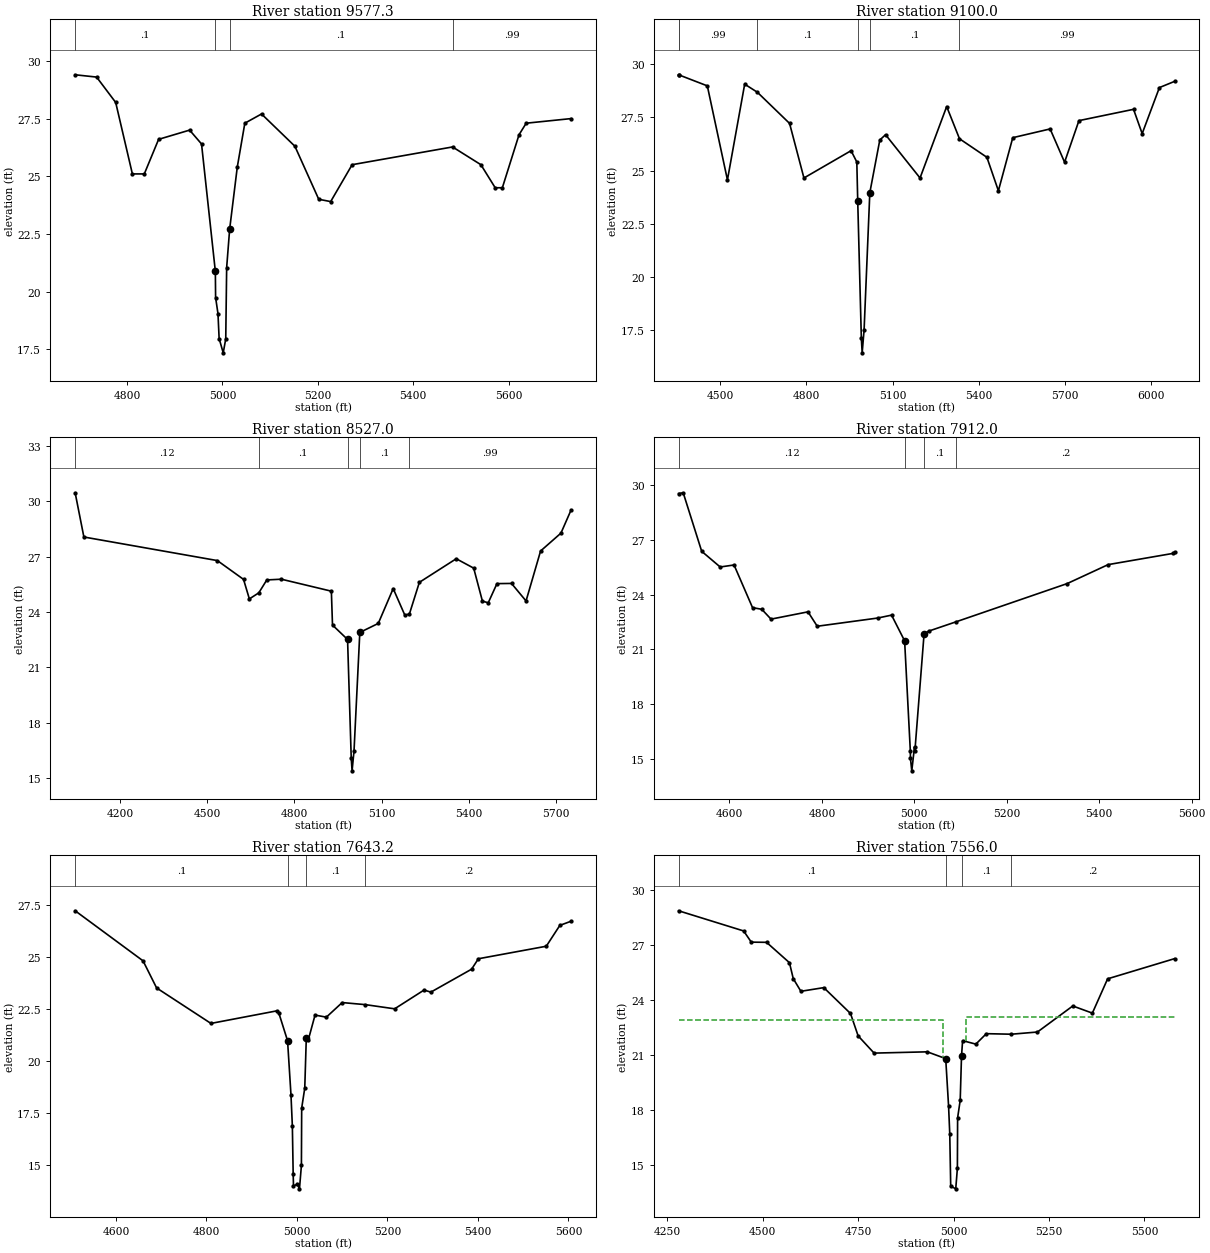
Type RM Length L Ch R = 1 ,9577.3,519.6,477.3,336.2
XS GIS Cut Line= 3
      3195635.14     13854591.02      3195289.46     13854580.55
      3194595.50     13854562.22
BEGIN DESCRIPTION:
Cross Section 9577.3 - Interpolated
END DESCRIPTION:
#Sta/Elev= 30
  4691.1    29.4  4736.1    29.3  4776.1    28.2  4811.1    25.1  4836.1    25.1
  4866.1    26.6  4931.1      27  4956.1    26.4  4985.1   20.87  4985.6   19.74
  4990.6   19.04    4993   17.96  5001.6   17.34  5006.9   17.95  5008.8   21.04
  5015.1   22.71  5031.1    25.4  5046.9    27.3  5081.9    27.7  5151.9    26.3
  5201.9      24  5226.9    23.9  5271.9    25.5  5482.5   26.27  5541.9    25.5
  5571.9    24.5  5586.9    24.5  5621.9    26.8  5636.9    27.3  5731.1    27.5
#Mann= 4 , 1 , 0
 4691.10     0.1       0  4985.1    0.04       0  5015.1     0.1       0
  5482.5    0.99       0
Bank Sta=4985.10,5015.10
Exp/Cntr=0.3,0.1

Type RM Length L Ch R = 1 ,9100.0,596.4,573,532.6
XS GIS Cut Line= 6
      3195688.00     13854135.91      3195432.48     13854154.83
      3195148.57     13854159.56      3194812.62     13854363.03
      3194448.27     13854528.64      3194055.53     13854528.64
BEGIN DESCRIPTION:
Cross Section 9100 - Interpolated
END DESCRIPTION:
#Sta/Elev= 30
  4355.6   29.49  4355.7   29.49  4455.6   28.97  4525.6   24.56  4585.6   29.05
  4629.8   28.67  4741.8   27.21  4791.8   24.65  4955.8   25.93  4975.8    25.4
 4978.95   23.58 4991.55   17.14 4994.45   16.45 5001.15   17.53 5021.05   23.96
  5055.8   26.43  5075.8   26.68  5195.8   24.65  5288.5      28  5333.1   26.49
  5428.5   25.62  5468.5   24.05  5518.5   26.54  5648.5   26.95  5698.8   25.39
  5748.8   27.34  5938.8   27.87  5968.8   26.73  6028.8   28.89  6081.5   29.18
#Mann= 6 , 1 , 0
 4355.60     0.2       0  4355.7    0.99       0  4629.8     0.1       0
 4978.95    0.04       0 5021.05     0.1       0  5333.1    0.99       0
Bank Sta=4978.95,5021.05
Exp/Cntr=0.3,0.1

Type RM Length L Ch R = 1 ,8527.0,493.4,615,740.6
XS GIS Cut Line= 6
      3195518.48     13853449.06      3195043.22     13853564.00
      3194702.80     13853758.53      3194554.70     13853911.05
      3194386.70     13854048.10      3194025.29     13854207.26
BEGIN DESCRIPTION:
Cross Section 8527
Located At: 2ND XS DS WOODFOREST
END DESCRIPTION:
#Sta/Elev= 30
    4046   30.47    4076   28.07    4535   26.79    4625   25.77    4645   24.71
  4677.5   25.04    4705   25.74    4755   25.78    4927   25.13  4930.9   23.29
  4982.7   22.51  4995.3   16.07  4998.2   15.38  5004.9   16.46  5024.8   22.89
  5088.3   23.38  5139.6   25.27  5179.6   23.83  5195.3   23.89  5229.6   25.61
  5356.4   26.89  5416.4   26.38  5446.4   24.59  5466.4    24.5  5496.4   25.54
  5546.4   25.55  5596.4    24.6  5646.4   27.31  5716.4   28.28  5751.4   29.54
#Mann= 5 , 1 , 0
 4046.00    0.12       0  4677.5     0.1       0  4982.7    0.04       0
  5024.8     0.1       0  5195.3    0.99       0
Bank Sta=4982.70,5024.80
Exp/Cntr=0.3,0.1

Type RM Length L Ch R = 1 ,7912.0,255.8,268.8,273.6
XS GIS Cut Line= 3
      3194986.73     13853341.48      3194557.16     13853309.06
      3193919.98     13853228.07
BEGIN DESCRIPTION:
Cross Section 7912 - Interpolated
END DESCRIPTION:
#Sta/Elev= 25
  4489.9   29.54  4499.9   29.58  4539.9   26.37  4579.9   25.51  4609.9   25.62
  4649.9   23.28  4669.9   23.19  4689.9   22.65  4769.9   23.05  4789.9   22.26
  4920.7   22.71  4950.7   22.87 4978.95   21.46 4991.35    15.4 4991.55   15.02
 4994.45   14.33 5000.35   15.65 5001.15   15.41 5021.05   21.84  5030.7   21.99
    5091   22.51  5330.7    24.6  5419.3   25.64  5560.7   26.26    5563   26.33
#Mann= 4 , 1 , 0
 4489.90    0.12       0 4978.95    0.04       0 5021.05     0.1       0
    5091     0.2       0
Bank Sta=4978.95,5021.05
Exp/Cntr=0.3,0.1

Type RM Length L Ch R = 1 ,7643.2,80.9,87.2,89.5
XS GIS Cut Line= 3
      3195019.73     13853119.30      3194417.43     13853017.17
      3193932.96     13852996.22
BEGIN DESCRIPTION:
Cross Section 7643.2 - Interpolated
END DESCRIPTION:
#Sta/Elev= 30
    4510    27.2    4660    24.8    4690    23.5    4810    21.8    4955    22.4
    4960    22.3  4979.3   20.97  4986.8   18.39  4989.9   16.88  4991.7   14.59
  4992.4   14.02  5000.9   14.08  5005.6   13.87  5009.9   14.99  5010.5   17.74
  5017.3    18.7  5020.7    21.1    5025      21    5040    22.2    5065    22.1
    5100    22.8  5151.3    22.7  5215.9    22.5  5280.9    23.4  5295.9    23.3
  5385.9    24.4  5400.9    24.9  5550.9    25.5  5580.9    26.5  5605.8    26.7
#Mann= 4 , 1 , 0
 4510.00     0.1       0  4979.3    0.04       0  5020.7     0.1       0
  5151.3     0.2       0
Bank Sta=4979.30,5020.70
Exp/Cntr=0.5,0.3

Type RM Length L Ch R = 1 ,7556.0,48,48,48
XS GIS Cut Line= 6
      3195260.30     13853102.94      3195022.54     13853057.01
      3194606.48     13852965.15      3194258.97     13852896.63
      3194166.84     13852945.56      3193994.57     13852960.84
BEGIN DESCRIPTION:
Upstream Section of Bridge/Culvert/Weir
END DESCRIPTION:
#Sta/Elev= 30
  4279.3   28.88  4449.8   27.78  4469.8   27.17  4509.8   27.16  4569.8   26.05
  4579.8   25.18  4599.8   24.49  4659.8   24.69  4729.8   23.28  4749.8   22.06
  4791.6   21.12    4931   21.19  4979.3   20.82  4986.8   18.24  4989.9   16.73
  4992.4   13.87  5005.6   13.72  5009.9   14.84  5010.5   17.59  5017.3   18.55
  5020.7   20.95  5023.6    21.8  5058.3   21.61  5085.8   22.18  5151.3   22.15
  5219.7   22.27  5312.3   23.69  5363.6    23.3  5403.6   25.17    5579   26.27
#Mann= 4 , 1 , 0
 4279.30     0.1       0  4979.3    0.04       0  5020.7     0.1       0
  5151.3     0.2       0
#XS Ineff= 2 , 0
       0  4972.5    22.9    5032       0    23.1
Bank Sta=4979.30,5020.70
Exp/Cntr=0.5,0.3