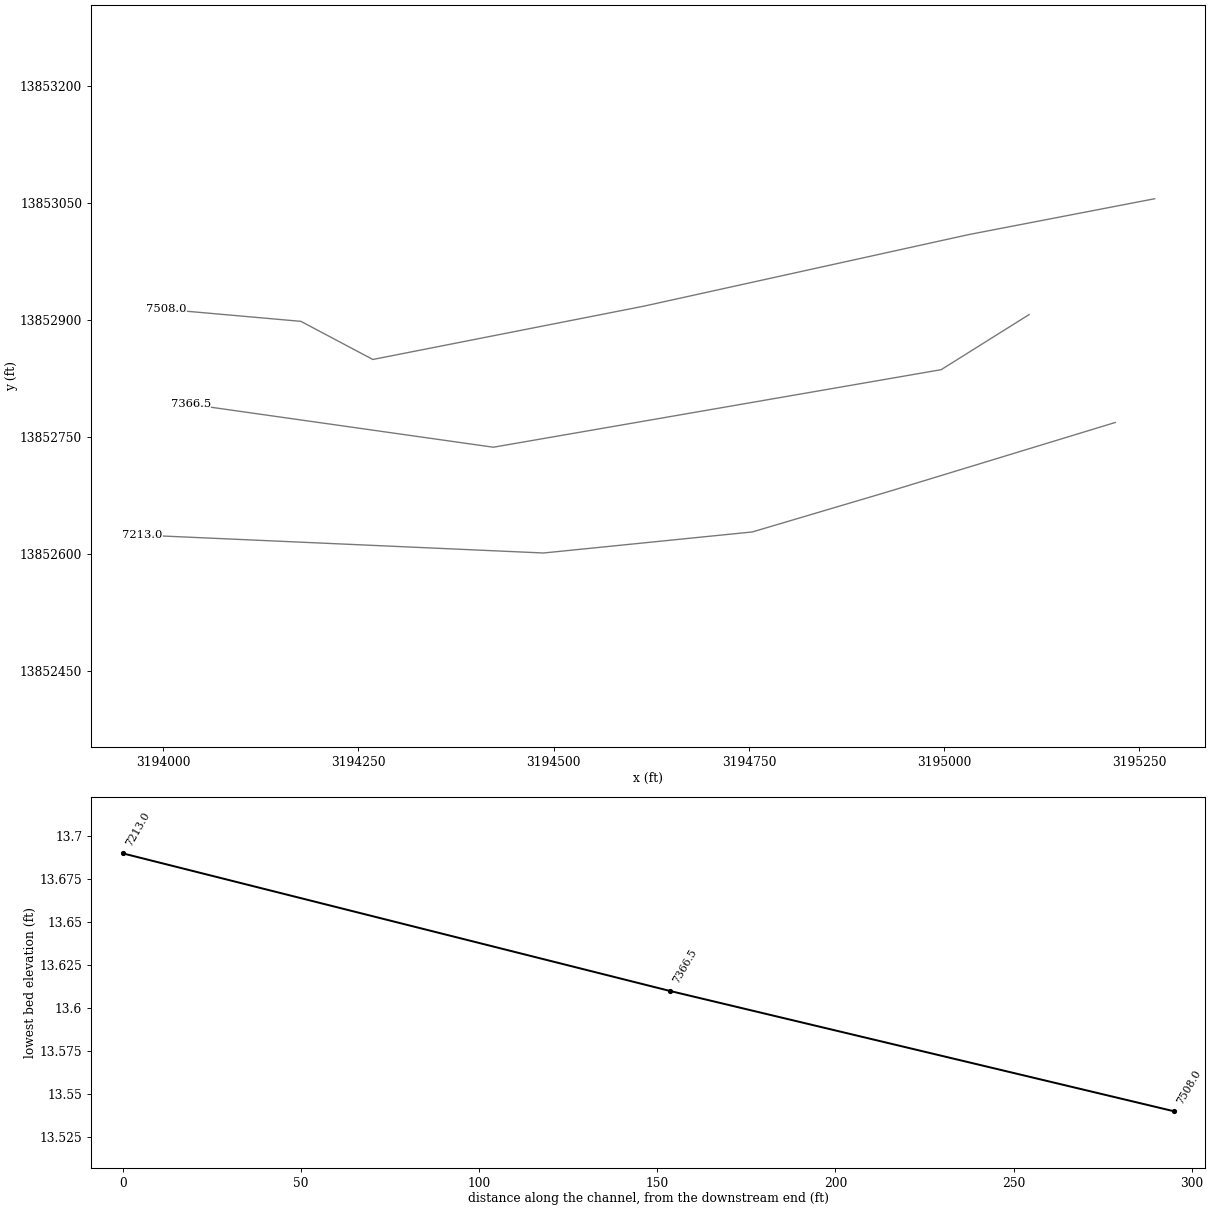
HEC-RAS study N104-00-00.PRJ: N104-00-00

--- N104-00-00.g01 (geometry) --- (continued)

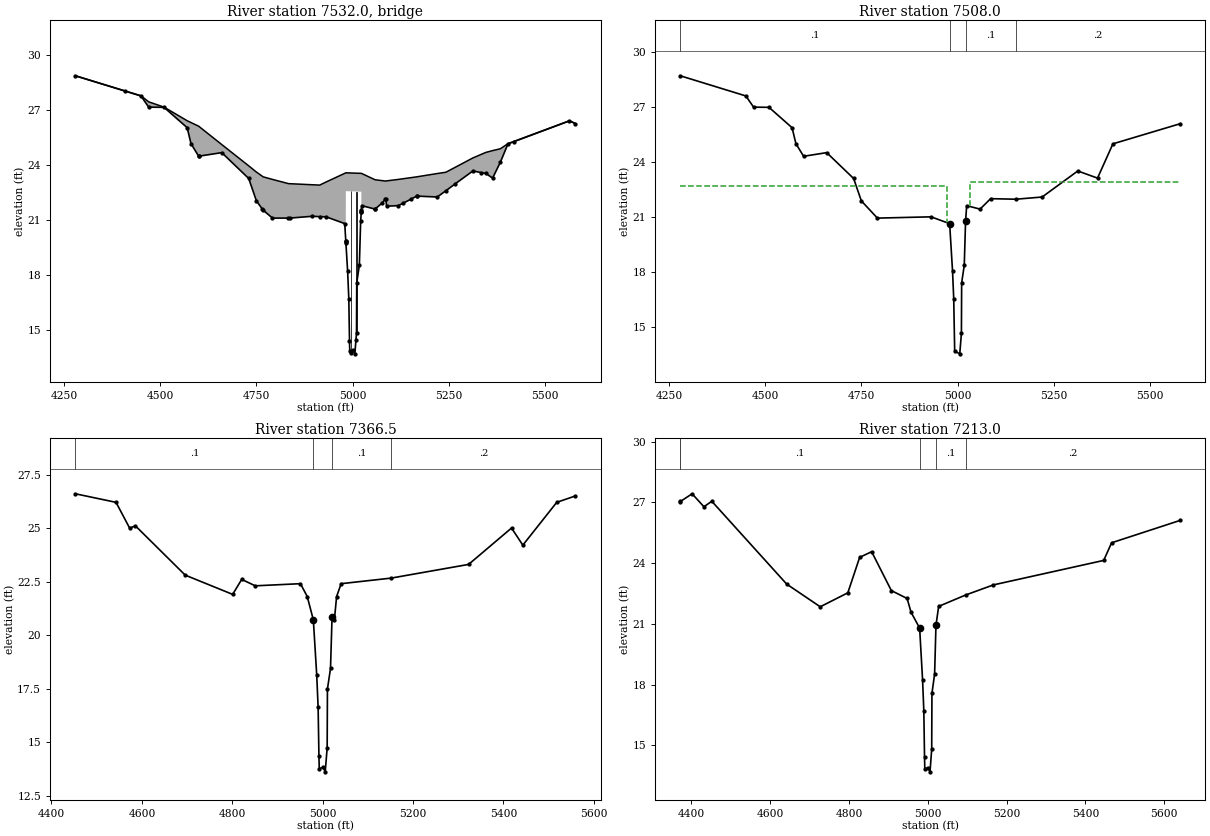
Type RM Length L Ch R = 3 ,7532.0,,,
BEGIN DESCRIPTION:
EAST BRENTWOOD ROAD
Structure ID: N04-9
END DESCRIPTION:
Bridge Culvert--1,0,-1,-1, 0
Deck Dist Width WeirC Skew NumUp NumDn MinLoCord MaxHiCord MaxSubmerge Is_Ogee
10,28,2.6,, 35, 35,,,0.95,0,1,1,,
  4279.3  4449.8  4469.8  4509.8  4569.8  4579.8  4599.8  4659.8  4729.8  4749.8
  4767.4  4791.6  4833.1  4914.2    4931  4979.3 4982.11  4982.2 5022.49  5022.6
  5023.6  5058.3  5085.8  5088.2  5118.5  5166.4  5219.7  5242.1  5312.3  5345.7
  5363.6  5383.6  5403.6  5563.4    5579
   28.86   27.77   27.44   27.15   26.41   26.31   26.11   25.11   23.95   23.61
   23.35   23.21   22.98    22.9   23.07   23.54   23.57   23.57   23.54   23.54
   23.53   23.19   23.12   23.13   23.21   23.35   23.53    23.6   24.38   24.68
   24.78   24.88   25.16   26.41   26.25
   28.86   27.76   27.15   27.14   26.03   25.16   24.47   24.67   23.26   22.04
   21.53    21.1    21.1   21.18   21.17    20.8   19.83   22.57   22.54   21.49
   21.78   21.59   22.16   21.75   21.78    22.3   22.25   22.59   23.67   23.54
   23.28   24.14   25.15    26.4   26.25
  4279.3  4449.8  4469.8  4509.8  4569.8  4579.8  4599.8  4659.8  4729.8  4749.8
  4767.4  4791.6  4833.1  4914.2    4931  4979.3 4982.11  4982.2 5022.49  5022.6
  5023.6  5058.3  5085.8  5088.2  5118.5  5166.4  5219.7  5242.1  5312.3  5345.7
  5363.6  5383.6  5403.6  5563.4    5579
   28.86   27.77   27.44   27.15   26.41   26.31   26.11   25.11   23.95   23.61
   23.35   23.21   22.98    22.9   23.07   23.54   23.57   23.57   23.54   23.54
   23.53   23.19   23.12   23.13   23.21   23.35   23.53    23.6   24.38   24.68
   24.78   24.88   25.16   26.41   26.25
    28.7    27.6   26.99   26.98   25.87      25   24.31   24.51    23.1   21.88
   21.37   20.94   20.94   21.02   21.01   20.64   19.67   22.41   22.38   21.33
   21.62   21.43      22   21.59   21.62   22.14   22.09   22.43   23.51   23.38
   23.12   23.98   24.99   26.24   26.09
Pier Skew, UpSta & Num, DnSta & Num=,4996.1, 2 ,4996.1, 2 , 0 , 0 , 0 ,,
     1.5     1.5
   12.79   23.56
     1.5     1.5
   12.63    23.4
Pier Skew, UpSta & Num, DnSta & Num=,5009.9, 2 ,5009.9, 2 , 0 , 0 , 0 ,,
     1.5     1.5
   13.63   23.55
     1.5     1.5
   13.47   23.39
BR Coef= 1 , 1 , 0 ,1.25, 0 ,,,0.8,0,2,0,
Wspro=,,,, 1 ,,,, 0 ,,,, 0 ,,,,-1 ,-1 ,-1 , 0 , 0 , 0 , 0 , 0
BC Design=,, 0 ,, 0 ,,,,,,
BR U #Sta/Elev= 65
  4279.3   28.86  4409.3   28.02  4449.8   27.76  4469.8   27.15  4509.8   27.14
  4569.8   26.03  4579.8   25.16  4599.8   24.47  4601.4   24.48  4659.8   24.67
  4729.8   23.26  4749.8   22.04  4764.9    21.6  4767.4   21.53  4791.6    21.1
  4833.1    21.1  4836.1    21.1  4895.3    21.2  4914.2   21.18    4931   21.17
  4979.3    20.8    4982   19.87 4982.11   19.83  4982.2    19.8  4982.3   19.77
  4986.8   18.22  4989.9   16.71  4991.7   14.42  4992.4   13.85  4996.1   13.77
  5000.9   13.91  5005.6    13.7  5008.4   14.44  5009.9   14.82  5010.5   17.57
  5017.3   18.53  5020.7   20.93  5022.4   21.43 5022.49   21.45  5022.6   21.49
  5022.7   21.52  5023.6   21.78  5058.3   21.59  5058.6    21.6    5077   21.93
  5084.6   22.13  5085.8   22.16  5088.2   21.75  5118.5   21.78    5130    21.9
  5151.3   22.13  5166.4    22.3  5166.6    22.3  5219.7   22.25  5242.1   22.59
  5264.6   22.94  5312.3   23.67  5334.2   23.58  5345.7   23.54  5363.6   23.28
  5383.6   24.14  5403.6   25.15  5419.1   25.27  5563.4    26.4    5579   26.25
BR U #Mann= 4
 4279.30     0.1  4979.3    0.04  5020.7     0.1  5151.3     0.2
BR U Banks=4979.30,5020.70
BR D #Sta/Elev= 65
  4279.3    28.7  4409.3   27.86  4449.8    27.6  4469.8   26.99  4509.8   26.98
  4569.8   25.87  4579.8      25  4599.8   24.31  4601.4   24.32  4659.8   24.51
  4729.8    23.1  4749.8   21.88  4764.9   21.44  4767.4   21.37  4791.6   20.94
  4833.1   20.94  4836.1   20.94  4895.3   21.04  4914.2   21.02    4931   21.01
  4979.3   20.64    4982   19.71 4982.11   19.67  4982.2   19.64  4982.3   19.61
  4986.8   18.06  4989.9   16.55  4991.7   14.26  4992.4   13.69  4996.1   13.61
  5000.9   13.75  5005.6   13.54  5008.4   14.28  5009.9   14.66  5010.5   17.41
  5017.3   18.37  5020.7   20.77  5022.4   21.27 5022.49   21.29  5022.6   21.33
  5022.7   21.36  5023.6   21.62  5058.3   21.43  5058.6   21.44    5077   21.77
  5084.6   21.97  5085.8      22  5088.2   21.59  5118.5   21.62    5130   21.74
  5151.3   21.97  5166.4   22.14  5166.6   22.14  5219.7   22.09  5242.1   22.43
  5264.6   22.78  5312.3   23.51  5334.2   23.42  5345.7   23.38  5363.6   23.12
  5383.6   23.98  5403.6   24.99  5419.1   25.11  5563.4   26.24    5579   26.09
BR D #Mann= 4
 4279.30     0.1  4979.3    0.04  5020.7     0.1  5151.3     0.2
BR D Banks=4979.30,5020.70

Type RM Length L Ch R = 1 ,7508.0,141.5,141.5,141.5
XS GIS Cut Line= 6
      3195269.72     13853055.88      3195031.96     13853009.95
      3194615.90     13852918.09      3194268.39     13852849.57
      3194176.26     13852898.50      3194003.99     13852913.78
BEGIN DESCRIPTION:
Downstream Section of Bridge/Culvert/Weir
END DESCRIPTION:
#Sta/Elev= 30
  4279.3    28.7  4449.8    27.6  4469.8   26.99  4509.8   26.98  4569.8   25.87
  4579.8      25  4599.8   24.31  4659.8   24.51  4729.8    23.1  4749.8   21.88
  4791.6   20.94    4931   21.01  4979.3   20.64  4986.8   18.06  4989.9   16.55
  4992.4   13.69  5005.6   13.54  5009.9   14.66  5010.5   17.41  5017.3   18.37
  5020.7   20.77  5023.6   21.62  5058.3   21.43  5085.8      22  5151.3   21.97
  5219.7   22.09  5312.3   23.51  5363.6   23.12  5403.6   24.99    5579   26.09
#Mann= 4 , 1 , 0
 4279.30     0.1       0  4979.3    0.04       0  5020.7     0.1       0
  5151.3     0.2       0
#XS Ineff= 2 , 0
       0  4972.5    22.7    5032       0    22.9
Bank Sta=4979.30,5020.70
Exp/Cntr=0.5,0.3

Type RM Length L Ch R = 1 ,7366.5,162.6,153.5,145.3
XS GIS Cut Line= 4
      3195108.77     13852907.18      3194996.17     13852836.47
      3194422.66     13852736.96      3194035.09     13852791.96
BEGIN DESCRIPTION:
Cross Section 7366.5 - Interpolated
END DESCRIPTION:
#Sta/Elev= 30
  4452.8    26.6  4542.8    26.2  4572.8      25  4585.8    25.1  4695.8    22.8
  4800.8    21.9  4820.8    22.6  4850.8    22.3  4950.8    22.4  4965.8    21.8
  4979.3   20.71  4986.8   18.13  4989.9   16.62  4991.7   14.33  4992.4   13.76
  5000.9   13.82  5005.6   13.61  5009.9   14.73  5010.5   17.48  5017.3   18.44
  5020.7   20.84  5025.8    20.7  5030.8    21.8  5040.8    22.4  5151.3   22.66
  5322.8    23.3  5417.8      25  5442.8    24.2  5517.8    26.2  5559.3    26.5
#Mann= 4 , 1 , 0
 4452.80     0.1       0  4979.3    0.04       0  5020.7     0.1       0
  5151.3     0.2       0
Bank Sta=4979.30,5020.70
Exp/Cntr=0.3,0.1

Type RM Length L Ch R = 1 ,7213.0,261.1,299.6,331.2
XS GIS Cut Line= 5
      3195219.08     13852768.71      3194927.29     13852679.56
      3194754.38     13852628.22      3194486.91     13852601.21
      3193972.84     13852624.18
BEGIN DESCRIPTION:
Cross Section 7213 - Interpolated
END DESCRIPTION:
#Sta/Elev= 30
    4372   27.03  4372.4   27.04    4402   27.42    4432   26.78    4452   27.05
    4642   22.96  4727.1   21.84  4797.1   22.53  4827.1   24.28  4857.5   24.56
  4907.5   22.64  4947.5   22.25  4957.5   21.57  4979.3   20.79  4986.8   18.21
  4989.9    16.7  4991.7   14.41  4992.4   13.84  5000.9    13.9  5005.6   13.69
  5009.9   14.81  5010.5   17.56  5017.3   18.52  5020.7   20.92  5027.5   21.86
  5095.8   22.42  5166.3   22.92  5446.3   24.13  5466.3      25  5640.9   26.11
#Mann= 5 , 1 , 0
 4372.00     0.2       0  4372.4     0.1       0  4979.3    0.04       0
  5020.7     0.1       0  5095.8     0.2       0
Bank Sta=4979.30,5020.70
Exp/Cntr=0.3,0.1