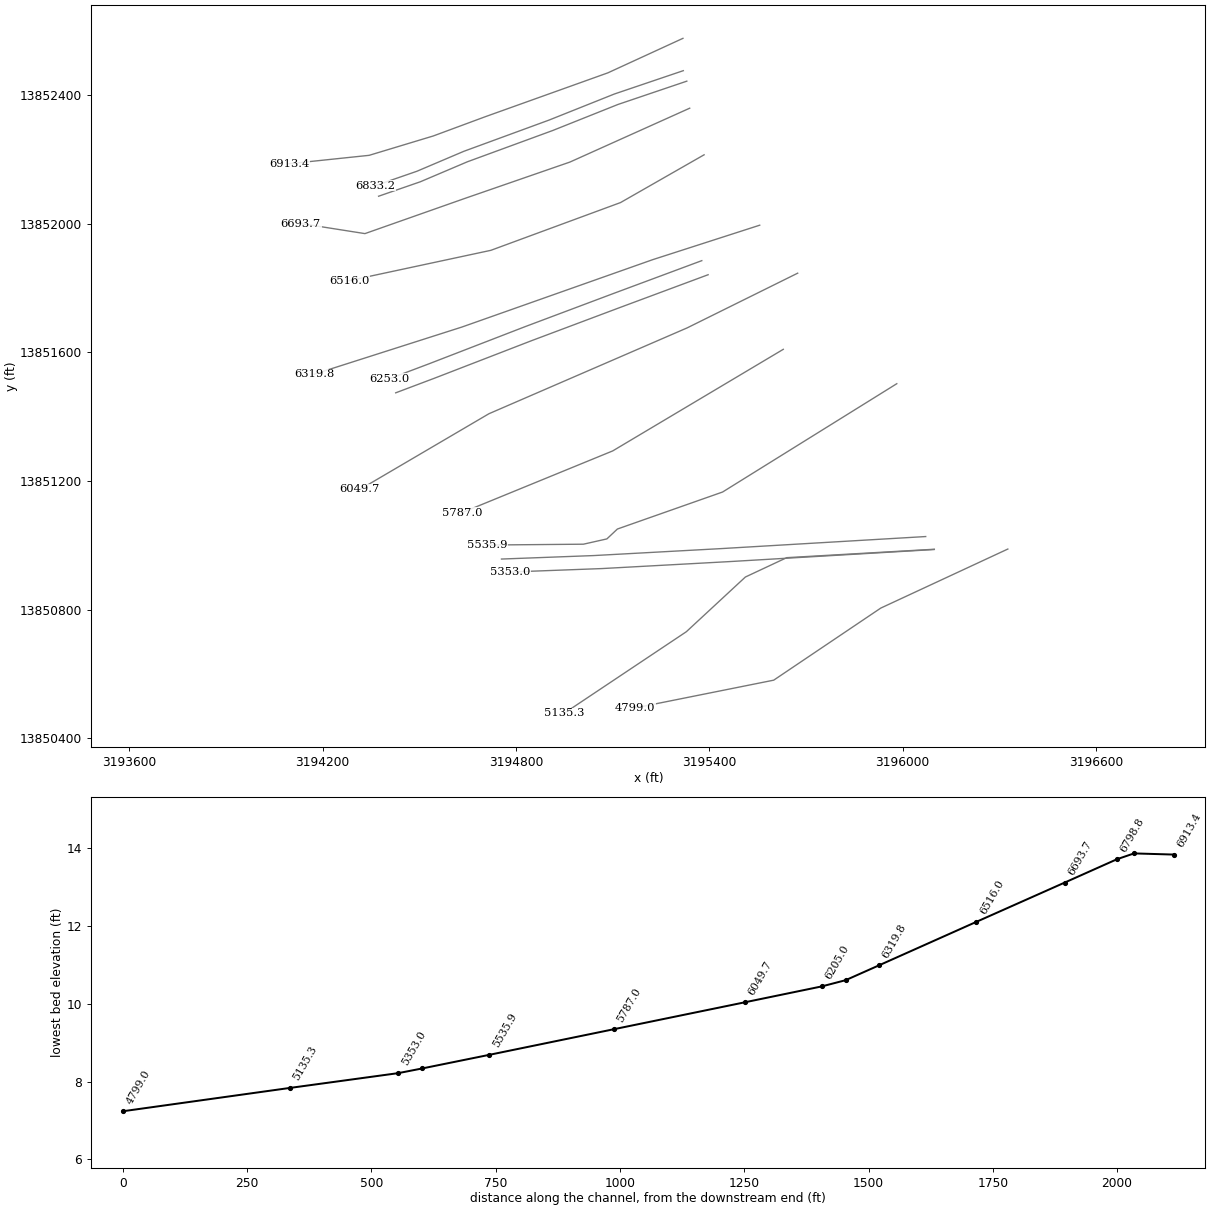
HEC-RAS study N104-00-00.PRJ: N104-00-00

--- N104-00-00.g01 (geometry) --- (continued)

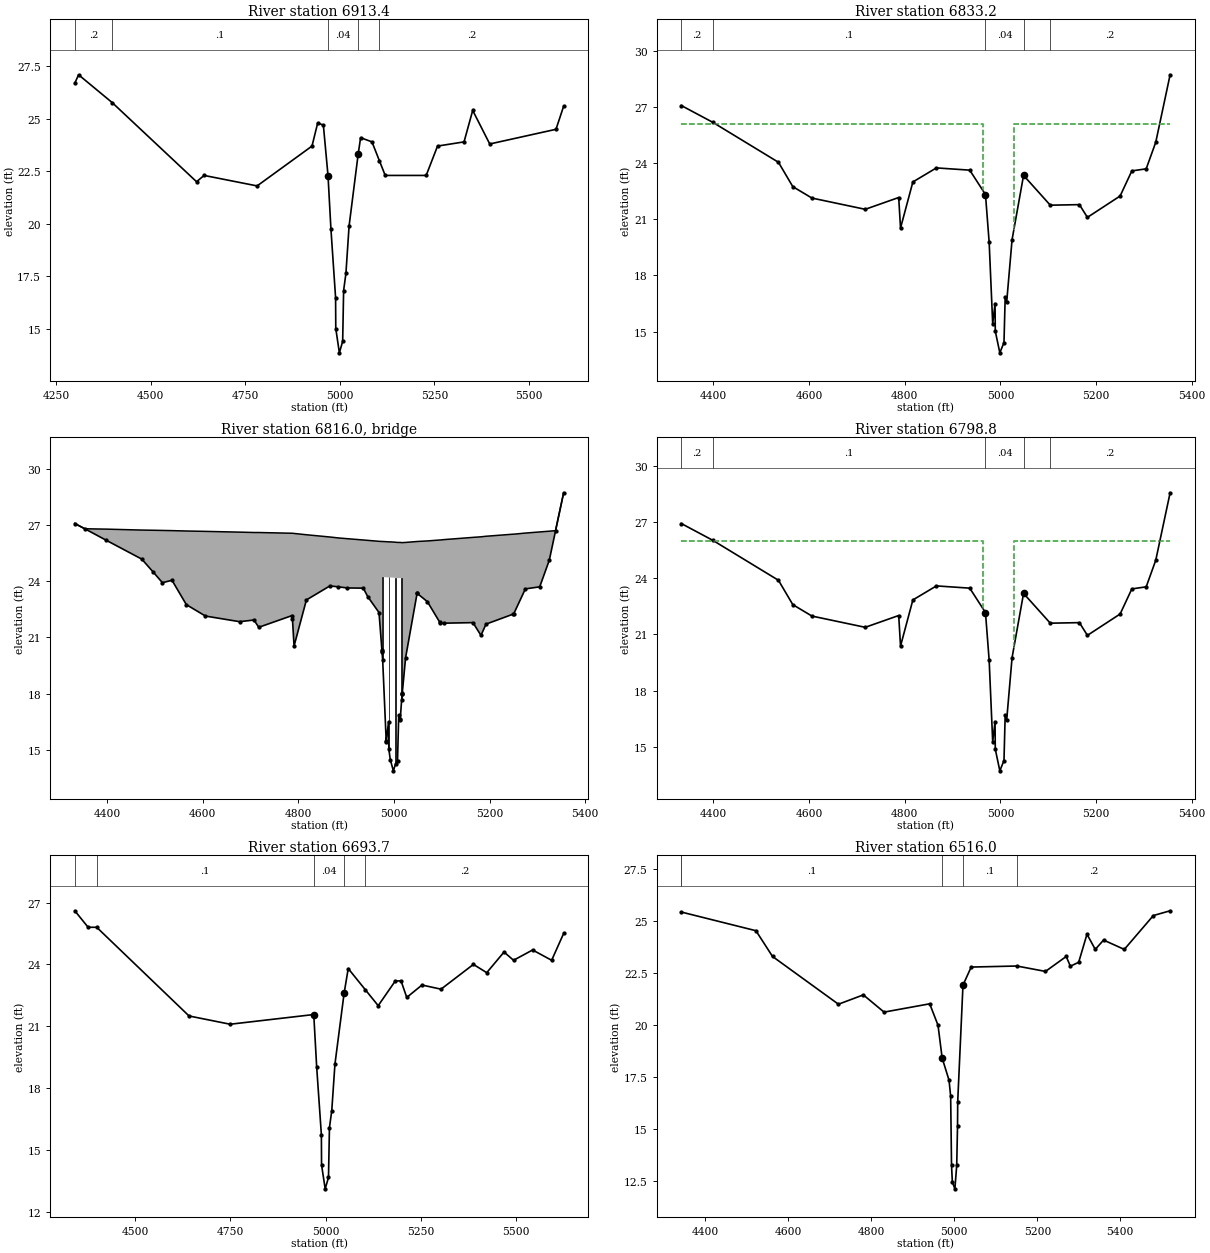
Type RM Length L Ch R = 1 ,6913.4,60.3,80.2,67.3
XS GIS Cut Line= 6
      3195318.27     13852577.22      3195085.20     13852469.85
      3194705.49     13852333.68      3194543.13     13852273.45
      3194344.10     13852213.22      3194095.32     13852187.03
BEGIN DESCRIPTION:
Cross Section 6913.4 - Interpolated
END DESCRIPTION:
#Sta/Elev= 30
  4299.9    26.7  4309.9    27.1  4398.9   25.77  4621.5      22  4641.5    22.3
  4781.5    21.8  4926.5    23.7  4941.5    24.8  4956.5    24.7  4968.8   22.29
  4976.5   19.74  4988.8   16.47  4989.3      15  4998.8   13.84  5007.5   14.39
    5010   16.81  5016.1   17.63  5024.4   19.88  5048.4   23.31  5054.9    24.1
  5084.9    23.9  5104.3   23.01  5119.9    22.3  5228.1    22.3  5258.1    23.7
  5328.1    23.9    5351    25.4    5396    23.8    5571    24.5  5591.2    25.6
#Mann= 5 , 1 , 0
 4299.90     0.2       0  4398.9     0.1       0  4968.8    0.04       0
  5048.4     0.1       0  5104.3     0.2       0
Bank Sta=4968.80,5048.40
Exp/Cntr=0.5,0.3

Type RM Length L Ch R = 1 ,6833.2,34.4,34.4,34.4
XS GIS Cut Line= 6
      3195319.35     13852476.62      3195105.57     13852404.09
      3194902.94     13852323.04      3194638.17     13852225.78
      3194492.28     13852163.64      3194362.52     13852118.62
BEGIN DESCRIPTION:
Upstream Section of Bridge/Culvert/Weir
END DESCRIPTION:
#Sta/Elev= 30
  4332.8   27.07  4398.9   26.17    4536   24.04    4566   22.74    4606   22.13
  4717.4   21.53  4787.4   22.16  4791.2   20.53    4817   22.99  4866.2   23.74
  4935.9   23.62  4968.8   22.32  4976.5   19.77  4983.9   15.42  4988.8    16.5
  4989.3   15.03  4998.8   13.87  5007.5   14.42    5010   16.84  5013.1   16.57
  5024.4   19.91  5048.4   23.34  5104.3   21.75  5165.2   21.78  5181.9    21.1
  5250.3   22.24  5274.8   23.58  5304.8   23.69  5324.8   25.11  5354.8   28.71
#Mann= 5 , 1 , 0
 4332.80     0.2       0  4398.9     0.1       0  4968.8    0.04       0
  5048.4     0.1       0  5104.3     0.2       0
#XS Ineff= 2 , 0
       0    4964    26.1    5028       0    26.1
Bank Sta=4968.80,5048.40
Exp/Cntr=0.5,0.3

Type RM Length L Ch R = 3 ,6816.0,,,
BEGIN DESCRIPTION:
UNION PACIFIC RAILROAD
Structure ID: N04-8
END DESCRIPTION:
Bridge Culvert--1,0,-1,-1, 0
Deck Dist Width WeirC Skew NumUp NumDn MinLoCord MaxHiCord MaxSubmerge Is_Ogee
10,14.4,2.6,,58,58,,,0.95,0,1,1,,
  4332.8  4353.7  4398.9  4472.8    4496    4516    4536    4566    4606  4677.4
  4707.4  4717.4  4787.4  4787.9  4791.2    4817  4866.2  4883.8  4902.7  4935.9
  4945.4  4968.8  4974.9 4975.01  4975.1  4976.5  4983.8  4983.9  4988.8  4989.3
  4992.4  4998.8  5003.4  5007.5    5010  5013.1  5013.2  5016.1 5017.19  5017.3
  5017.4  5024.4  5048.4  5048.6  5069.9  5095.8  5096.9  5104.3  5165.2  5181.9
  5192.6  5248.9  5250.3  5274.8  5304.8  5324.8  5337.8  5354.8
   27.08    26.8   26.78   26.73   26.72   26.71    26.7   26.68   26.66   26.62
    26.6    26.6   26.56   26.56   26.55   26.48   26.36   26.31   26.27    26.2
   26.18   26.13   26.12   26.12   26.12   26.12   26.11   26.11    26.1    26.1
    26.1   26.09   26.08   26.07   26.07   26.07   26.07   26.06   26.06   26.06
   26.06   26.07   26.12   26.12   26.15    26.2    26.2   26.22   26.34   26.37
    26.4   26.51   26.51   26.57   26.63   26.67    26.7   28.72
   27.08    26.8   26.18   25.18   24.51   23.92   24.05   22.75   22.14   21.84
   21.93   21.54   22.17   21.96   20.54      23   23.75    23.7   23.64   23.63
   23.17   22.33   20.31   20.27   24.22   24.22   24.21   24.21    24.2    24.2
    24.2   24.19   24.18   24.17   24.17   24.17   24.17   24.16   24.16      18
   18.02   19.92   23.35   23.35   22.91   21.81   21.76   21.76   21.79   21.11
   21.71   22.24   22.25   23.59    23.7   25.12   26.68   28.72
  4332.8  4353.7  4398.9  4472.8    4496    4516    4536    4566    4606  4677.4
  4707.4  4717.4  4787.4  4787.9  4791.2    4817  4866.2  4883.8  4902.7  4935.9
  4945.4  4968.8  4974.9 4975.01  4975.1  4976.5  4983.8  4983.9  4988.8  4989.3
  4992.4  4998.8  5003.4  5007.5    5010  5013.1  5013.2  5016.1 5017.19  5017.3
  5017.4  5024.4  5048.4  5048.6  5069.9  5095.8  5096.9  5104.3  5165.2  5181.9
  5192.6  5248.9  5250.3  5274.8  5304.8  5324.8  5337.8  5354.8
   27.08    26.8   26.78   26.73   26.72   26.71    26.7   26.68   26.66   26.62
    26.6    26.6   26.56   26.56   26.55   26.48   26.36   26.31   26.27    26.2
   26.18   26.13   26.12   26.12   26.12   26.12   26.11   26.11    26.1    26.1
    26.1   26.09   26.08   26.07   26.07   26.07   26.07   26.06   26.06   26.06
   26.06   26.07   26.12   26.12   26.15    26.2    26.2   26.22   26.34   26.37
    26.4   26.51   26.51   26.57   26.63   26.67    26.7   28.72
   26.98    26.7   26.08   25.08   24.41   23.82   23.95   22.65   22.04   21.74
   21.83   21.44   22.07   21.86   20.44    22.9   23.65    23.6   23.54   23.53
   23.07   22.23   20.21   20.17   24.12   24.12   24.11   24.11    24.1    24.1
    24.1   24.09   24.08   24.07   24.07   24.07   24.07   24.06   24.06    17.9
   17.92   19.82   23.25   23.25   22.81   21.71   21.66   21.66   21.69   21.01
   21.61   22.14   22.15   23.49    23.6   25.02   26.58   28.62
Pier Skew, UpSta & Num, DnSta & Num=,4976.5, 2 ,4976.5, 2 , 0 , 0 , 0 ,,
       1       1
   18.49   25.22
       1       1
   18.39   25.12
Pier Skew, UpSta & Num, DnSta & Num=,4989.3, 2 ,4989.3, 2 , 0 , 0 , 0 ,,
       1       1
   13.95    25.2
       1       1
   13.85    25.1
Pier Skew, UpSta & Num, DnSta & Num=,5003.4, 2 ,5003.4, 2 , 0 , 0 , 0 ,,
       1       1
   13.21   25.18
       1       1
   13.11   25.08
Pier Skew, UpSta & Num, DnSta & Num=,5016.1, 2 ,5016.1, 2 , 0 , 0 , 0 ,,
       1       1
   16.49   25.16
       1       1
   16.39   25.06
Abutment Skew #Up #Dn=, 2 , 2
 4974.90 4983.90
   24.22   15.43
 4974.90 4983.90
   24.12   15.33
Abutment Skew #Up #Dn=, 2 , 2
 5013.20 5017.39
   16.62   24.16
 5013.20 5017.39
   16.52   24.06
BR Coef= 1 , 1 , 0 ,1.25, 0 ,,,0.8,0,2,1,
Wspro=,,,, 1 ,,,, 0 ,,,, 0 ,,,,-1 ,-1 ,-1 , 0 , 0 , 0 , 0 , 0
BC Design=,, 0 ,, 0 ,,,,,,
BR U #Sta/Elev= 58
  4332.8   27.08  4353.7    26.8  4398.9   26.18  4472.8   25.18    4496   24.51
    4516   23.92    4536   24.05    4566   22.75    4606   22.14  4677.4   21.84
  4707.4   21.93  4717.4   21.54  4787.4   22.17  4787.9   21.96  4791.2   20.54
    4817      23  4866.2   23.75  4883.8    23.7  4902.7   23.64  4935.9   23.63
  4945.4   23.17  4968.8   22.33  4974.9   20.31 4975.01   20.27  4975.1   20.24
  4976.5   19.78  4983.8   15.49  4983.9   15.43  4988.8   16.51  4989.3   15.04
  4992.4   14.48  4998.8   13.88  5003.4   14.25  5007.5   14.43    5010   16.85
  5013.1   16.58  5013.2   16.62  5016.1   17.67 5017.19   17.97  5017.3      18
  5017.4   18.02  5024.4   19.92  5048.4   23.35  5048.6   23.35  5069.9   22.91
  5095.8   21.81  5096.9   21.76  5104.3   21.76  5165.2   21.79  5181.9   21.11
  5192.6   21.71  5248.9   22.24  5250.3   22.25  5274.8   23.59  5304.8    23.7
  5324.8   25.12  5337.8   26.68  5354.8   28.72
BR U #Mann= 5
 4332.80     0.2  4398.9     0.1  4968.8    0.04  5048.4     0.1  5104.3     0.2
BR U Banks=4968.80,5048.40
BR D #Sta/Elev= 58
  4332.8   26.98  4353.7    26.7  4398.9   26.08  4472.8   25.08    4496   24.41
    4516   23.82    4536   23.95    4566   22.65    4606   22.04  4677.4   21.74
  4707.4   21.83  4717.4   21.44  4787.4   22.07  4787.9   21.86  4791.2   20.44
    4817    22.9  4866.2   23.65  4883.8    23.6  4902.7   23.54  4935.9   23.53
  4945.4   23.07  4968.8   22.23  4974.9   20.21 4975.01   20.17  4975.1   20.14
  4976.5   19.68  4983.8   15.39  4983.9   15.33  4988.8   16.41  4989.3   14.94
  4992.4   14.38  4998.8   13.78  5003.4   14.15  5007.5   14.33    5010   16.75
  5013.1   16.48  5013.2   16.52  5016.1   17.57 5017.19   17.87  5017.3    17.9
  5017.4   17.92  5024.4   19.82  5048.4   23.25  5048.6   23.25  5069.9   22.81
  5095.8   21.71  5096.9   21.66  5104.3   21.66  5165.2   21.69  5181.9   21.01
  5192.6   21.61  5248.9   22.14  5250.3   22.15  5274.8   23.49  5304.8    23.6
  5324.8   25.02  5337.8   26.58  5354.8   28.62
BR D #Mann= 5
 4332.80     0.2  4398.9     0.1  4968.8    0.04  5048.4     0.1  5104.3     0.2
BR D Banks=4968.80,5048.40

Type RM Length L Ch R = 1 ,6798.8,105.1,105.1,105.1
XS GIS Cut Line= 6
      3195330.23     13852443.99      3195116.45     13852371.45
      3194913.82     13852290.40      3194649.05     13852193.14
      3194503.16     13852131.00      3194373.40     13852085.99
BEGIN DESCRIPTION:
Downstream Section of Bridge/Culvert/Weir
END DESCRIPTION:
#Sta/Elev= 30
  4332.8   26.92  4398.9   26.02    4536   23.89    4566   22.59    4606   21.98
  4717.4   21.38  4787.4   22.01  4791.2   20.38    4817   22.84  4866.2   23.59
  4935.9   23.47  4968.8   22.17  4976.5   19.62  4983.9   15.27  4988.8   16.35
  4989.3   14.88  4998.8   13.72  5007.5   14.27    5010   16.69  5013.1   16.42
  5024.4   19.76  5048.4   23.19  5104.3    21.6  5165.2   21.63  5181.9   20.95
  5250.3   22.09  5274.8   23.43  5304.8   23.54  5324.8   24.96  5354.8   28.56
#Mann= 5 , 1 , 0
 4332.80     0.2       0  4398.9     0.1       0  4968.8    0.04       0
  5048.4     0.1       0  5104.3     0.2       0
#XS Ineff= 2 , 0
       0    4964      26    5028       0      26
Bank Sta=4968.80,5048.40
Exp/Cntr=0.5,0.3

Type RM Length L Ch R = 1 ,6693.7,174.5,177.7,180.5
XS GIS Cut Line= 5
      3195339.22     13852359.87      3194967.36     13852192.27
      3194642.64     13852079.66      3194331.01     13851969.67
      3194131.99     13852001.10
BEGIN DESCRIPTION:
Cross Section 6693.7 - Interpolated
END DESCRIPTION:
#Sta/Elev= 30
  4341.4    26.6  4376.4    25.8  4398.9    25.8  4641.4    21.5  4749.3    21.1
  4968.8   21.57  4976.5   19.02  4988.8   15.75  4989.3   14.28  4998.8   13.12
  5007.5   13.67    5010   16.09  5016.1   16.91  5024.4   19.16  5048.4   22.59
  5059.3    23.8  5104.3   22.77    5138      22    5183    23.2    5198    23.2
    5213    22.4    5253      23    5303    22.8    5388      24    5423    23.6
  5468.4    24.6  5493.4    24.2  5543.4    24.7  5593.4    24.2  5624.9    25.5
#Mann= 5 , 1 , 0
 4341.40     0.2       0  4398.9     0.1       0  4968.8    0.04       0
  5048.4     0.1       0  5104.3     0.2       0
Bank Sta=4968.80,5048.40
Exp/Cntr=0.3,0.1

Type RM Length L Ch R = 1 ,6516.0,168.4,196.2,166.1
XS GIS Cut Line= 4
      3195383.88     13852214.86      3195124.52     13852066.27
      3194721.96     13851917.67      3194281.58     13851823.11
BEGIN DESCRIPTION:
Cross Section 6516 - Interpolated
END DESCRIPTION:
#Sta/Elev= 30
  4341.7   25.44  4521.7   24.54  4561.7    23.3  4720.6      21  4780.6   21.45
  4830.6   20.62  4940.6   21.02  4960.6   19.99  4970.6   18.41  4987.2   17.34
  4991.1   16.57  4993.2   13.24  4995.2   12.43  5001.3   12.11  5005.7   13.24
  5007.7   15.16  5008.1   16.31  5020.8   21.92  5040.6   22.79  5150.6   22.84
  5219.7   22.58  5269.7    23.3  5279.7   22.83  5299.7   23.02  5319.7   24.37
  5339.7   23.64  5359.7   24.09  5409.7   23.64  5479.7   25.27  5520.1    25.5
#Mann= 5 , 1 , 0
 4341.70     0.2       0  4341.7     0.1       0  4970.6    0.04       0
  5020.8     0.1       0  5150.6     0.2       0
Bank Sta=4970.60,5020.80
Exp/Cntr=0.3,0.1

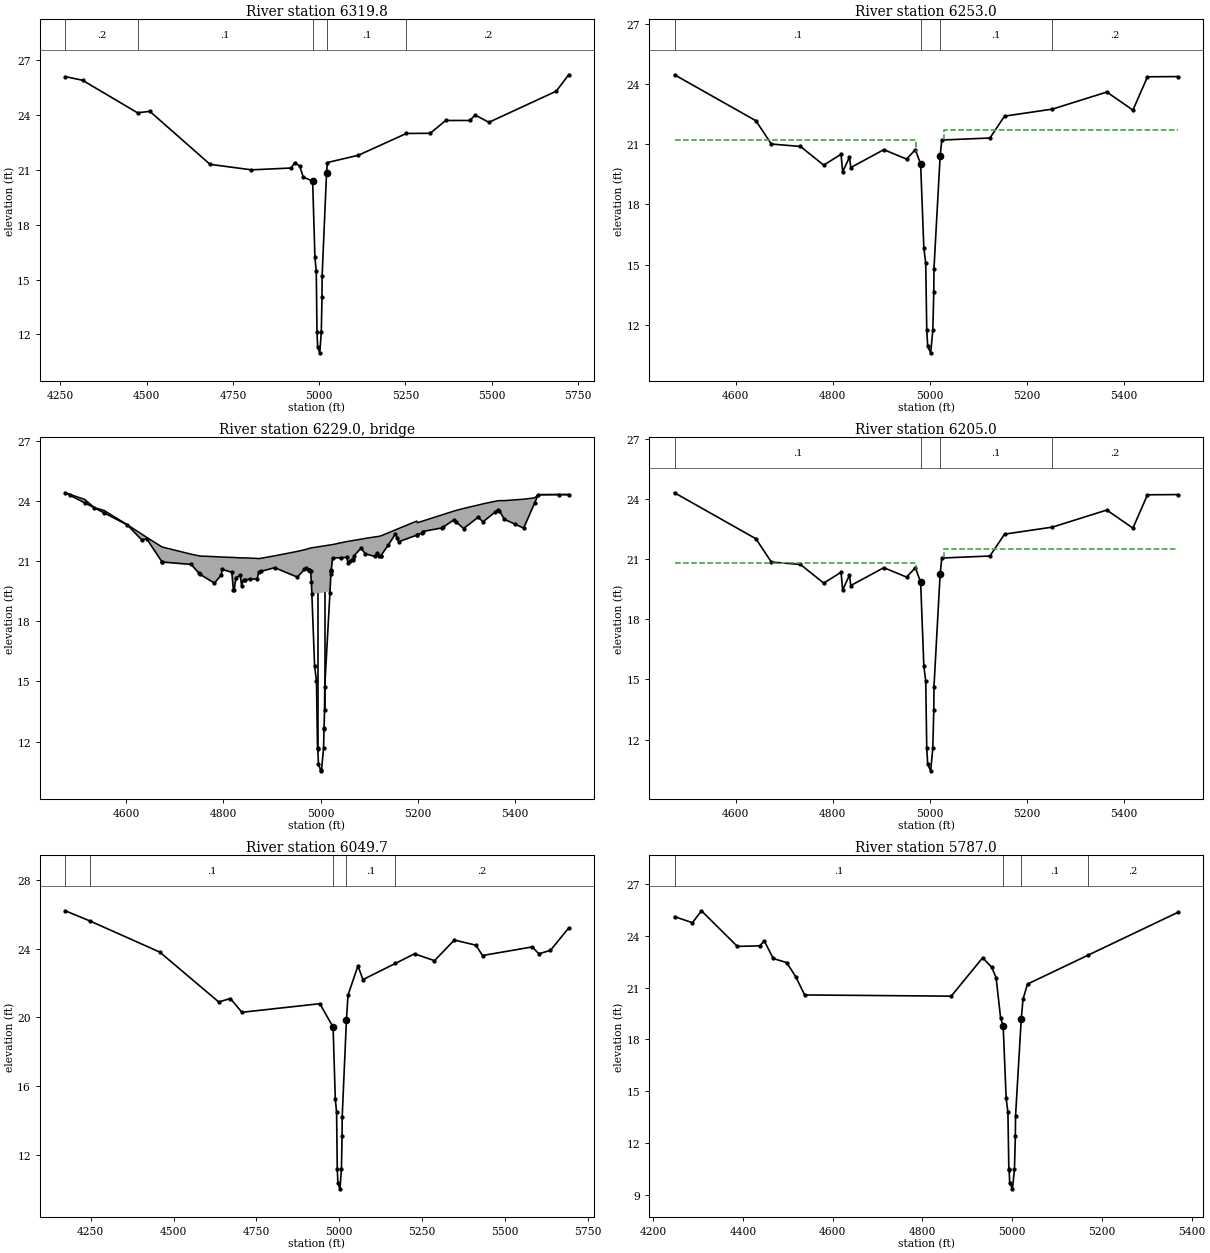
Type RM Length L Ch R = 1 ,6319.8,55.5,66.8,63
XS GIS Cut Line= 4
      3195556.57     13851995.86      3195224.00     13851888.49
      3194632.16     13851679.00      3194173.89     13851532.35
BEGIN DESCRIPTION:
Cross Section 6319.8 - Interpolated
END DESCRIPTION:
#Sta/Elev= 30
  4264.4    26.1  4314.4    25.9  4473.7   24.12  4509.4    24.2  4683.9    21.3
  4803.9      21  4918.9    21.1  4928.9    21.4  4943.9    21.2  4953.9    20.6
  4981.1   20.39  4987.7   16.22  4991.6   15.45  4993.7   12.12  4995.7   11.31
  5001.8   10.99  5006.2   12.12  5008.2   14.04  5008.6   15.19  5021.3    20.8
  5023.9    21.4  5113.9    21.8  5252.7   22.99  5321.7      23  5366.7    23.7
  5436.7    23.7  5451.7      24  5491.7    23.6  5686.7    25.3  5722.9    26.2
#Mann= 5 , 1 , 0
 4264.40     0.2       0  4473.7     0.1       0  4981.1    0.04       0
  5021.3     0.1       0  5252.7     0.2       0
Bank Sta=4981.10,5021.30
Exp/Cntr=0.5,0.3

Type RM Length L Ch R = 1 ,6253.0,48,48,48
XS GIS Cut Line= 5
      3195376.76     13851885.54      3195101.19     13851782.87
      3194828.31     13851680.21      3194528.42     13851564.03
      3194406.85     13851518.10
BEGIN DESCRIPTION:
Upstream Section of Bridge/Culvert/Weir
END DESCRIPTION:
#Sta/Elev= 30
    4474   24.46  4641.7   22.17  4673.5   21.01  4733.5   20.89  4781.4   19.96
  4817.1    20.5  4820.4   19.62  4834.5   20.36  4837.2   19.84  4905.3   20.73
  4952.1   20.26  4970.2   20.73  4981.1   20.01  4987.7   15.84  4991.6   15.07
  4993.7   11.74  4995.7   10.93  5001.8   10.61  5006.2   11.74  5008.2   13.66
  5008.6   14.81  5021.3   20.42  5024.7   21.21  5123.9   21.31    5154    22.4
  5252.7   22.75  5364.7    23.6  5418.5    22.7  5448.5   24.36  5511.2   24.37
#Mann= 4 , 1 , 0
 4474.00     0.1       0  4981.1    0.04       0  5021.3     0.1       0
  5252.7     0.2       0
#XS Ineff= 2 , 0
       0    4972    21.2    5029       0    21.7
Bank Sta=4981.10,5021.30
Exp/Cntr=0.5,0.3

Type RM Length L Ch R = 3 ,6229.0,,,
BEGIN DESCRIPTION:
AVENUE C
Structure ID: N04-7
END DESCRIPTION:
Bridge Culvert--1,0,-1,-1, 0
Deck Dist Width WeirC Skew NumUp NumDn MinLoCord MaxHiCord MaxSubmerge Is_Ogee
10,28,2.6,, 60, 60,,,0.95,0,1,1,,
    4474    4514    4534    4554  4601.7  4631.7  4641.7  4673.5  4733.5  4751.4
  4781.4  4795.3  4797.5  4817.1  4820.4    4822  4825.8  4834.5  4837.2  4841.5
  4869.4  4872.9  4905.3  4952.1  4970.2  4979.5  4981.1  4982.1  5019.3  5021.3
  5024.7  5053.8  5056.7  5066.3  5067.6    5069  5083.3  5092.3  5111.5  5117.3
  5119.7  5123.9    5154  5158.2  5160.9  5198.1  5199.6  5210.2  5250.2  5274.7
  5294.7  5324.7  5334.7  5364.7  5368.5  5378.5  5418.5  5441.2  5448.5  5511.2
    24.4   24.07   23.66   23.52   22.81   22.34   22.18    21.7   21.34   21.25
   21.22    21.2    21.2   21.18   21.18   21.18   21.17   21.16   21.16   21.16
   21.13   21.12   21.26   21.48   21.58   21.65   21.66   21.66    21.8   21.81
   21.82   21.97   21.98   22.02   22.03   22.03   22.09   22.13    22.2   22.22
   22.23   22.25   22.55   22.59   22.62   22.99   22.91   22.99    23.3   23.49
   23.62   23.79   23.85      24   24.01   24.01   24.08   24.15   24.31   24.31
    24.4    23.9   23.65    23.4    22.8   22.05   22.11   20.95   20.83   20.34
    19.9    20.3   20.58   20.44   19.56   19.57   20.16    20.3   19.78   20.06
   20.11   20.46   20.67    20.2   20.67   20.48   19.95   19.35   19.47   20.36
   21.15   21.18    20.9   21.12   21.04   21.26   21.64   21.36   21.23    21.4
   21.25   21.25   22.34   22.17   21.96   22.29   22.31   22.47   22.65   23.05
   22.62   23.18   22.95   23.54   23.51   23.08   22.64    23.9    24.3   24.31
    4474    4514    4534    4554  4601.7  4631.7  4641.7  4673.5  4733.5  4751.4
  4781.4  4795.3  4797.5  4817.1  4820.4    4822  4825.8  4834.5  4837.2  4841.5
  4869.4  4872.9  4905.3  4952.1  4970.2  4979.5  4981.1  4982.1  5019.3  5021.3
  5024.7  5053.8  5056.7  5066.3  5067.6    5069  5083.3  5092.3  5111.5  5117.3
  5119.7  5123.9    5154  5158.2  5160.9  5198.1  5199.6  5210.2  5250.2  5274.7
  5294.7  5324.7  5334.7  5364.7  5368.5  5378.5  5418.5  5441.2  5448.5  5511.2
    24.4   24.07   23.66   23.52   22.81   22.34   22.18    21.7   21.34   21.25
   21.22    21.2    21.2   21.18   21.18   21.18   21.17   21.16   21.16   21.16
   21.13   21.12   21.26   21.48   21.58   21.65   21.66   21.66    21.8   21.81
   21.82   21.97   21.98   22.02   22.03   22.03   22.09   22.13    22.2   22.22
   22.23   22.25   22.55   22.59   22.62   22.99   22.91   22.99    23.3   23.49
   23.62   23.79   23.85      24   24.01   24.01   24.08   24.15   24.31   24.31
   24.33   23.83   23.58   23.33   22.73   21.98   22.04   20.88   20.76   20.27
   19.83   20.23   20.51   20.37   19.49    19.5   20.09   20.23   19.71   19.99
   20.04   20.39    20.6   20.13    20.6   20.41   19.88   19.28    19.4   20.29
   21.08   21.11   20.83   21.05   20.97   21.19   21.57   21.29   21.16   21.33
   21.18   21.18   22.27    22.1   21.89   22.22   22.24    22.4   22.58   22.98
   22.55   23.11   22.88   23.47   23.44   23.01   22.57   23.83   24.23   24.24
Pier Skew, UpSta & Num, DnSta & Num=,4980.1, 2 ,4980.1, 2 , 0 , 0 , 0 ,,
     1.5     1.5
   19.03   21.48
     1.5     1.5
   18.96   21.41
Pier Skew, UpSta & Num, DnSta & Num=,4994.3, 2 ,4994.3, 2 , 0 , 0 , 0 ,,
     1.5     1.5
   10.24   20.38
     1.5     1.5
   10.17   20.31
Pier Skew, UpSta & Num, DnSta & Num=,5008.2, 2 ,5008.2, 2 , 0 , 0 , 0 ,,
     1.5     1.5
   11.93   20.43
     1.5     1.5
   11.86   20.36
Abutment Skew #Up #Dn=, 2 , 2
 5007.20 5022.09
   12.70   20.50
 5007.20 5022.09
   12.63   20.43
BR Coef= 1 , 1 , 0 ,1.25, 0 ,,,0.8,0,2,0,
Wspro=,,,, 1 ,,,, 0 ,,,, 0 ,,,,-1 ,-1 ,-1 , 0 , 0 , 0 , 0 , 0
BC Design=,, 0 ,, 0 ,,,,,,
BR U #Sta/Elev= 96
    4474    24.4    4484   24.27    4514    23.9    4534   23.65    4554    23.4
  4601.7    22.8  4631.7   22.05  4641.7   22.11  4673.5   20.95    4674   20.95
  4733.5   20.83  4749.5   20.39  4751.4   20.34  4781.4    19.9  4795.3    20.3
  4797.5   20.58  4817.1   20.44  4820.4   19.56    4822   19.57  4825.8   20.16
  4834.5    20.3  4837.2   19.78  4841.5   20.06  4843.7   20.07  4853.8   20.09
  4869.4   20.11  4872.9   20.46  4876.7   20.48  4905.3   20.67  4952.1    20.2
  4966.8   20.58  4970.2   20.67    4977   20.53 4977.11   20.53  4977.2   20.53
  4977.3   20.52  4979.5   20.48  4981.1   19.95  4982.1   19.35  4987.7   15.78
  4991.6   15.01  4993.7   11.68  4994.3   11.66  4995.7   10.87  5000.2   10.59
  5001.8   10.55  5006.2   11.68  5007.1   12.61  5007.2    12.7  5008.2    13.6
  5008.6   14.75  5019.3    19.4  5021.3   20.36 5021.89    20.5    5022   20.52
  5022.1   20.55  5024.7   21.15  5042.5   21.17  5053.8   21.18  5056.7    20.9
  5060.7   20.99  5066.3   21.12  5067.6   21.04    5069   21.26  5083.3   21.64
  5092.3   21.36  5111.5   21.23  5117.3    21.4  5119.7   21.25  5123.8   21.25
  5123.9   21.25  5139.4   21.79    5154   22.34  5158.2   22.17  5160.9   21.96
  5198.1   22.29  5199.6   22.31  5208.8   22.39  5210.2   22.47  5250.2   22.65
  5252.7   22.69  5274.7   23.05  5279.6   22.94  5294.7   22.62  5324.7   23.18
  5334.7   22.95  5359.6   23.44  5364.7   23.54  5368.5   23.51  5378.5   23.08
  5401.2   22.83  5418.5   22.64  5441.2    23.9  5448.5    24.3  5491.2   24.31
  5511.2   24.31
BR U #Mann= 4
 4474.00     0.1  4981.1    0.04  5021.3     0.1  5252.7     0.2
BR U Banks=4981.10,5021.30
BR D #Sta/Elev= 96
    4474   24.33    4484    24.2    4514   23.83    4534   23.58    4554   23.33
  4601.7   22.73  4631.7   21.98  4641.7   22.04  4673.5   20.88    4674   20.88
  4733.5   20.76  4749.5   20.32  4751.4   20.27  4781.4   19.83  4795.3   20.23
  4797.5   20.51  4817.1   20.37  4820.4   19.49    4822    19.5  4825.8   20.09
  4834.5   20.23  4837.2   19.71  4841.5   19.99  4843.7      20  4853.8   20.02
  4869.4   20.04  4872.9   20.39  4876.7   20.41  4905.3    20.6  4952.1   20.13
  4966.8   20.51  4970.2    20.6    4977   20.46 4977.11   20.46  4977.2   20.46
  4977.3   20.45  4979.5   20.41  4981.1   19.88  4982.1   19.28  4987.7   15.71
  4991.6   14.94  4993.7   11.61  4994.3   11.59  4995.7    10.8  5000.2   10.52
  5001.8   10.48  5006.2   11.61  5007.1   12.54  5007.2   12.63  5008.2   13.53
  5008.6   14.68  5019.3   19.33  5021.3   20.29 5021.89   20.43    5022   20.45
  5022.1   20.48  5024.7   21.08  5042.5    21.1  5053.8   21.11  5056.7   20.83
  5060.7   20.92  5066.3   21.05  5067.6   20.97    5069   21.19  5083.3   21.57
  5092.3   21.29  5111.5   21.16  5117.3   21.33  5119.7   21.18  5123.8   21.18
  5123.9   21.18  5139.4   21.72    5154   22.27  5158.2    22.1  5160.9   21.89
  5198.1   22.22  5199.6   22.24  5208.8   22.32  5210.2    22.4  5250.2   22.58
  5252.7   22.62  5274.7   22.98  5279.6   22.87  5294.7   22.55  5324.7   23.11
  5334.7   22.88  5359.6   23.37  5364.7   23.47  5368.5   23.44  5378.5   23.01
  5401.2   22.76  5418.5   22.57  5441.2   23.83  5448.5   24.23  5491.2   24.24
  5511.2   24.24
BR D #Mann= 4
 4474.00     0.1  4981.1    0.04  5021.3     0.1  5252.7     0.2
BR D Banks=4981.10,5021.30

Type RM Length L Ch R = 1 ,6205.0,155.3,155.3,155.3
XS GIS Cut Line= 5
      3195396.40     13851841.74      3195120.83     13851739.07
      3194847.95     13851636.41      3194548.06     13851520.23
      3194426.49     13851474.30
BEGIN DESCRIPTION:
Downstream Section of Bridge/Culvert/Weir
END DESCRIPTION:
#Sta/Elev= 30
    4474    24.3  4641.7   22.01  4673.5   20.85  4733.5   20.73  4781.4    19.8
  4817.1   20.34  4820.4   19.46  4834.5    20.2  4837.2   19.68  4905.3   20.57
  4952.1    20.1  4970.2   20.57  4981.1   19.85  4987.7   15.68  4991.6   14.91
  4993.7   11.58  4995.7   10.77  5001.8   10.45  5006.2   11.58  5008.2    13.5
  5008.6   14.65  5021.3   20.26  5024.7   21.05  5123.9   21.15    5154   22.24
  5252.7   22.59  5364.7   23.44  5418.5   22.54  5448.5    24.2  5511.2   24.21
#Mann= 4 , 1 , 0
 4474.00     0.1       0  4981.1    0.04       0  5021.3     0.1       0
  5252.7     0.2       0
#XS Ineff= 2 , 0
       0    4972    20.8    5029       0    21.5
Bank Sta=4981.10,5021.30
Exp/Cntr=0.5,0.3

Type RM Length L Ch R = 1 ,6049.7,257.9,262.7,258.4
XS GIS Cut Line= 4
      3195674.42     13851846.59      3195331.36     13851676.38
      3194715.96     13851409.27      3194315.30     13851173.58
BEGIN DESCRIPTION:
Cross Section 6049.7 - Interpolated
END DESCRIPTION:
#Sta/Elev= 30
  4173.1    26.2  4247.2   25.61  4458.1    23.8  4636.1    20.9  4671.1    21.1
  4706.1    20.3  4941.1    20.8  4981.1   19.44  4987.7   15.27  4991.6    14.5
  4993.7   11.17  4995.7   10.36  5001.8   10.04  5006.2   11.17  5008.2   13.09
  5008.6   14.24  5021.3   19.85  5026.1    21.3  5056.1      23  5071.1    22.2
    5169   23.14  5226.9    23.7  5286.9    23.3  5346.9    24.5  5411.9    24.2
  5431.9    23.6  5581.9    24.1  5601.9    23.7  5636.9    23.9  5691.8    25.2
#Mann= 5 , 1 , 0
 4173.10     0.2       0  4247.2     0.1       0  4981.1    0.04       0
  5021.3     0.1       0    5169     0.2       0
Bank Sta=4981.10,5021.30
Exp/Cntr=0.3,0.1

Type RM Length L Ch R = 1 ,5787.0,249.3,251.1,242.2
XS GIS Cut Line= 3
      3195629.74     13851609.68      3195100.20     13851293.58
      3194632.80     13851101.75
BEGIN DESCRIPTION:
Cross Section 5787 - Interpolated
END DESCRIPTION:
#Sta/Elev= 30
  4247.4    25.1  4287.4   24.75  4307.4   25.44  4387.4   23.38  4437.4   23.41
  4447.4    23.7  4467.4   22.68  4497.4   22.44  4517.4   21.63  4537.4   20.57
  4864.1    20.5  4934.1   22.72  4954.1   22.18  4964.1   21.57  4974.1   19.25
  4979.9   18.75  4986.5   14.58  4990.4   13.81  4992.5   10.48  4993.1   10.46
  4994.5    9.67  5000.6    9.35    5005   10.48    5007    12.4  5007.4   13.55
  5020.1   19.16  5024.1   20.33  5034.1    21.2    5169   22.87  5369.3   25.35
#Mann= 4 , 1 , 0
 4247.40     0.1       0  4979.9    0.04       0  5020.1     0.1       0
    5169     0.2       0
Bank Sta=4979.90,5020.10
Exp/Cntr=0.3,0.1

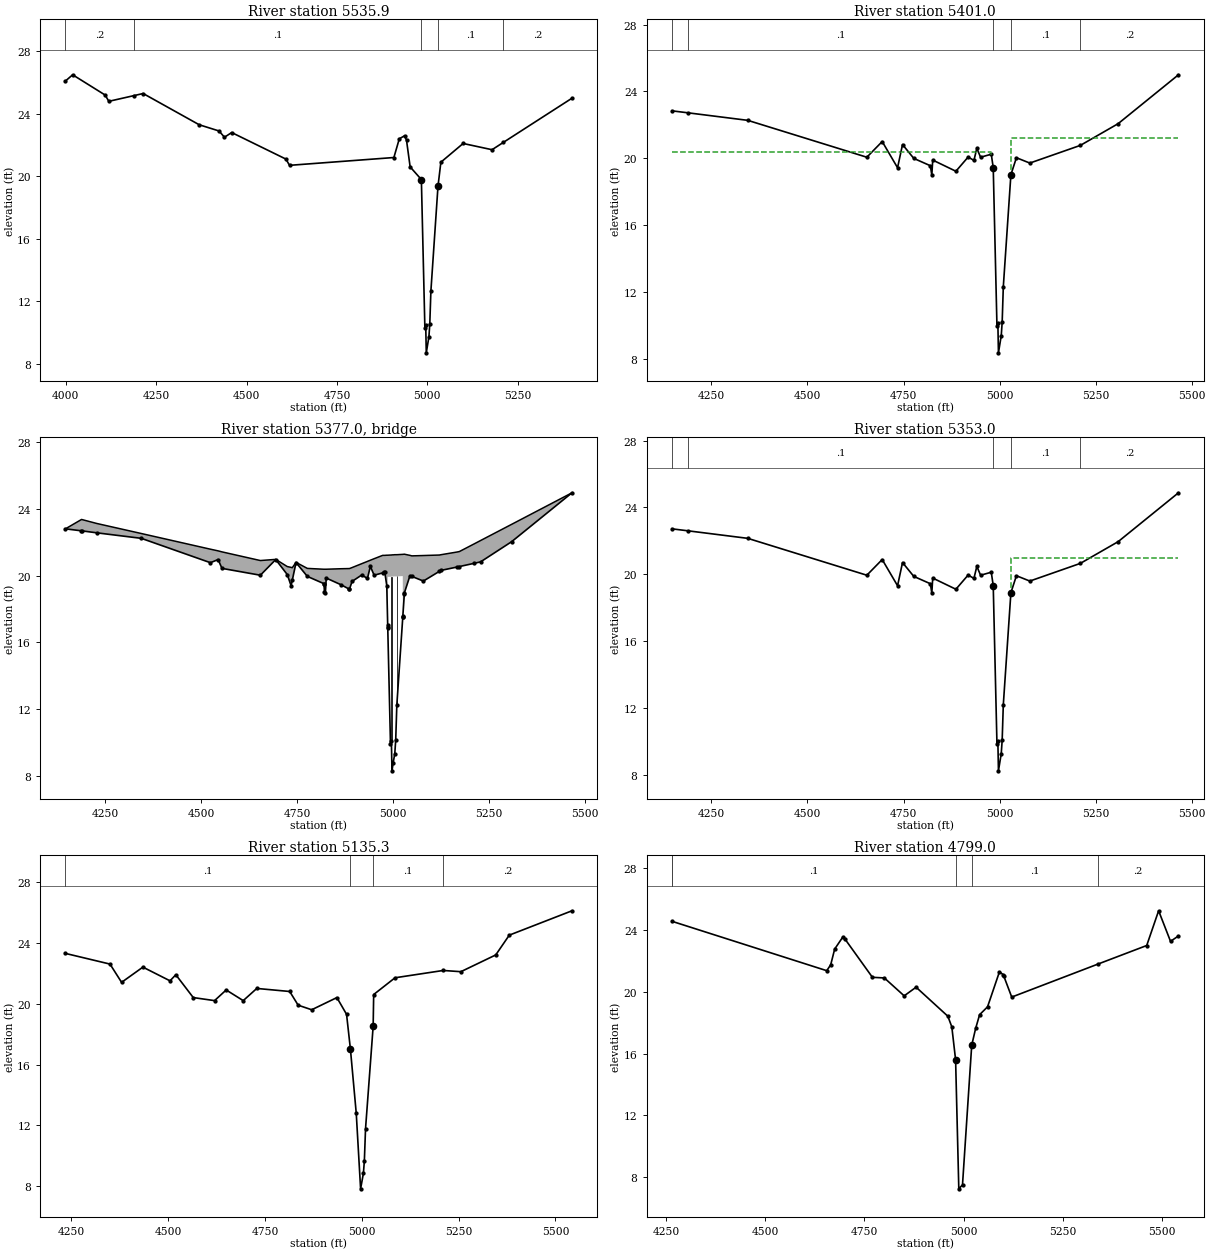
Type RM Length L Ch R = 1 ,5535.9,116.2,134.9,39.3
XS GIS Cut Line= 6
      3195982.09     13851502.71      3195441.35     13851165.72
      3195114.73     13851050.54      3195082.11     13851019.80
      3195009.26     13851003.36      3194710.78     13851000.76
BEGIN DESCRIPTION:
Cross Section 5535.9 - Interpolated
END DESCRIPTION:
#Sta/Elev= 30
  3998.8    26.1  4018.8    26.5  4108.8    25.2  4118.8    24.8  4189.3   25.17
  4213.8    25.3  4368.8    23.3  4423.8    22.9  4438.8    22.5  4458.8    22.8
  4608.8    21.1  4618.8    20.7  4907.5    21.2  4922.5    22.4  4937.5    22.6
  4942.5    22.3  4952.5    20.6 4983.55   19.79 4993.25    10.3 4995.58   10.49
 4997.14    8.69 5004.42    9.72 5006.84   10.53 5009.87   12.64 5029.53   19.36
  5037.5    20.9  5099.1    22.1  5179.1    21.7  5210.4   22.17  5400.3      25
#Mann= 5 , 1 , 0
 3998.80     0.2       0  4189.3     0.1       0 4983.55    0.04       0
 5029.53     0.1       0  5210.4     0.2       0
Bank Sta=4983.55,5029.53
Exp/Cntr=0.5,0.3

Type RM Length L Ch R = 1 ,5401.0,48,48,48
XS GIS Cut Line= 4
      3196071.89     13851027.16      3195435.77     13850989.58
      3195041.32     13850967.97      3194754.94     13850957.16
BEGIN DESCRIPTION:
Upstream Section of Bridge/Culvert/Weir
END DESCRIPTION:
#Sta/Elev= 30
    4147   22.84  4189.3   22.72  4344.5   22.27  4654.5   20.06  4694.5      21
  4734.5   19.43 4747.39   20.82 4776.75   19.99 4819.96   19.55 4823.68   18.98
 4826.02   19.89 4886.38   19.22 4918.16   20.07 4933.32   19.87 4940.85   20.59
 4950.64   20.06 4978.44   20.24 4983.55   19.44 4993.25    9.95 4995.58   10.14
 4997.14    8.34 5004.42    9.37 5006.84   10.18 5009.77   12.29 5029.53   19.01
 5043.91   20.03 5078.81   19.71  5210.4   20.77  5308.7   22.07  5465.8      25
#Mann= 5 , 1 , 0
 4147.00     0.2       0  4189.3     0.1       0 4983.55    0.04       0
 5029.53     0.1       0  5210.4     0.2       0
#XS Ineff= 2 , 0
       0    4979    20.4    5029       0    21.2
Bank Sta=4983.55,5029.53
Exp/Cntr=0.5,0.3

Type RM Length L Ch R = 3 ,5377.0,,,
BEGIN DESCRIPTION:
SOUTH BRENTWOOD ROAD, SKEW ANGLE OF 30 DEGREES
Structure ID: N04-6
END DESCRIPTION:
Bridge Culvert--1,0,-1,-1, 0
Deck Dist Width WeirC Skew NumUp NumDn MinLoCord MaxHiCord MaxSubmerge Is_Ogee
10,28,2.6,,58,58,,,0.95,0,1,1,,
    4147  4188.8  4189.3  4228.8  4344.5  4524.5  4544.5  4554.5  4654.5  4694.5
  4724.5  4734.5  4737.5 4747.39 4776.75  4819.4 4819.96 4821.43 4823.68 4826.02
 4865.34 4886.38  4886.5 4893.31 4918.16 4933.32 4940.85 4950.64  4972.9  4976.9
 4978.44 4983.55 4985.97 4986.06 4986.14 4993.25 4995.58 4997.14 5000.17 5004.42
 5006.84 5009.77 5025.19 5025.26 5025.37  5029.3 5029.53 5043.91  5048.8 5078.81
  5120.4 5124.88 5166.36  5172.7  5210.4 5227.84  5308.7  5465.8
   22.81   23.37   23.37   23.13   22.53   21.59   21.49   21.43   20.91   20.98
   20.55    20.5   20.48    20.8   20.44   20.39   20.39   20.39   20.39   20.39
   20.42   20.43   20.43   20.49   20.72   20.86   20.93   21.02   21.22   21.22
   21.22   21.23   21.23   21.23   21.23   21.24   21.24   21.25   21.25   21.26
   21.26   21.26   21.28   21.28   21.28   21.29   21.29   21.22   21.19   21.21
   21.24   21.26   21.42   21.45    21.9   22.11   23.08   24.97
   22.81   22.69   22.69   22.57   22.24   20.78   20.97   20.44   20.03   20.97
   20.07    19.4   19.72   20.79   19.96   19.53   19.52   19.03   18.95   19.86
   19.45   19.19    19.2   19.66   20.04   19.84   20.56   20.03   20.17    20.2
   20.21   19.41   17.04   19.93   19.93   19.94   19.94   19.95   19.95   19.96
   19.96   19.96   19.98   19.98   17.57    18.9   18.98      20   19.96   19.68
   20.26   20.32   20.52   20.55   20.74   20.83   22.04   24.97
    4147  4188.8  4189.3  4228.8  4344.5  4524.5  4544.5  4554.5  4654.5  4694.5
  4724.5  4734.5  4737.5 4747.39 4776.75  4819.4 4819.96 4821.43 4823.68 4826.02
 4865.34 4886.38  4886.5 4893.31 4918.16 4933.32 4940.85 4950.64  4972.9  4976.9
 4978.44 4983.55 4985.97 4986.06 4986.14 4993.25 4995.58 4997.14 5000.17 5004.42
 5006.84 5009.77 5025.19 5025.26 5025.37  5029.3 5029.53 5043.91  5048.8 5078.81
  5120.4 5124.88 5166.36  5172.7  5210.4 5227.84  5308.7  5465.8
   22.81   23.37   23.37   23.13   22.53   21.59   21.49   21.43   20.91   20.98
   20.55    20.5   20.48    20.8   20.44   20.39   20.39   20.39   20.39   20.39
   20.42   20.43   20.43   20.49   20.72   20.86   20.93   21.02   21.22   21.22
   21.22   21.23   21.23   21.23   21.23   21.24   21.24   21.25   21.25   21.26
   21.26   21.26   21.28   21.28   21.28   21.29   21.29   21.22   21.19   21.21
   21.24   21.26   21.42   21.45    21.9   22.11   23.08   24.97
   22.74   22.62   22.62    22.5   22.17   20.71    20.9   20.37   19.96    20.9
      20   19.33   19.65   20.72   19.89   19.46   19.45   18.96   18.88   19.79
   19.38   19.12   19.13   19.59   19.97   19.77   20.49   19.96    20.1   20.13
   20.14   19.34   16.97   19.86   19.86   19.87   19.87   19.88   19.88   19.89
   19.89   19.89   19.91   19.91    17.5   18.83   18.91   19.93   19.89   19.61
   20.19   20.25   20.45   20.48   20.67   20.76   21.97    24.9
Pier Skew, UpSta & Num, DnSta & Num=,4995.6, 2 ,4995.6, 2 , 0 , 0 , 0 ,,
     1.5     1.5
    8.24   20.94
     1.5     1.5
    8.17   20.87
Pier Skew, UpSta & Num, DnSta & Num=,5009.9, 2 ,5009.9, 2 , 0 , 0 , 0 ,,
     1.5     1.5
   10.79   20.96
     1.5     1.5
   10.72   20.89
BR Coef= 1 , 1 , 0 ,1.25, 0 ,,,0.8,0,2,0,
Wspro=,,,, 1 ,,,, 0 ,,,, 0 ,,,,-1 ,-1 ,-1 , 0 , 0 , 0 , 0 , 0
BC Design=,, 0 ,, 0 ,,,,,,
BR U #Sta/Elev= 58
    4147   22.81  4188.8   22.69  4189.3   22.69  4228.8   22.57  4344.5   22.24
  4524.5   20.78  4544.5   20.97  4554.5   20.44  4654.5   20.03  4694.5   20.97
  4724.5   20.07  4734.5    19.4  4737.5   19.72 4747.39   20.79 4776.75   19.96
  4819.4   19.53 4819.96   19.52 4821.43   19.03 4823.68   18.95 4826.02   19.86
 4865.34   19.45 4886.38   19.19  4886.5    19.2 4893.31   19.66 4918.16   20.04
 4933.32   19.84 4940.85   20.56 4950.64   20.03  4972.9   20.17  4976.9    20.2
 4978.44   20.21 4983.55   19.41 4985.97   17.04 4986.06   16.95 4986.14   16.88
 4993.25    9.92 4995.58   10.11 4997.14    8.31 5000.17    8.78 5004.42    9.34
 5006.84   10.15 5009.77   12.26 5025.19    17.5 5025.26   17.53 5025.37   17.57
  5029.3    18.9 5029.53   18.98 5043.91      20  5048.8   19.96 5078.81   19.68
  5120.4   20.26 5124.88   20.32 5166.36   20.52  5172.7   20.55  5210.4   20.74
 5227.84   20.83  5308.7   22.04  5465.8   24.97
BR U #Mann= 5
 4147.00     0.2  4189.3     0.1 4983.55    0.04 5029.53     0.1  5210.4     0.2
BR U Banks=4983.55,5029.53
BR D #Sta/Elev= 58
    4147   22.74  4188.8   22.62  4189.3   22.62  4228.8    22.5  4344.5   22.17
  4524.5   20.71  4544.5    20.9  4554.5   20.37  4654.5   19.96  4694.5    20.9
  4724.5      20  4734.5   19.33  4737.5   19.65 4747.39   20.72 4776.75   19.89
  4819.4   19.46 4819.96   19.45 4821.43   18.96 4823.68   18.88 4826.02   19.79
 4865.34   19.38 4886.38   19.12  4886.5   19.13 4893.31   19.59 4918.16   19.97
 4933.32   19.77 4940.85   20.49 4950.64   19.96  4972.9    20.1  4976.9   20.13
 4978.44   20.14 4983.55   19.34 4985.97   16.97 4986.06   16.88 4986.14   16.81
 4993.25    9.85 4995.58   10.04 4997.14    8.24 5000.17    8.71 5004.42    9.27
 5006.84   10.08 5009.77   12.19 5025.19   17.43 5025.26   17.46 5025.37    17.5
  5029.3   18.83 5029.53   18.91 5043.91   19.93  5048.8   19.89 5078.81   19.61
  5120.4   20.19 5124.88   20.25 5166.36   20.45  5172.7   20.48  5210.4   20.67
 5227.84   20.76  5308.7   21.97  5465.8    24.9
BR D #Mann= 5
 4147.00     0.2  4189.3     0.1 4983.55    0.04 5029.53     0.1  5210.4     0.2
BR D Banks=4983.55,5029.53

Type RM Length L Ch R = 1 ,5353.0,217.7,217.7,217.7
XS GIS Cut Line= 4
      3196097.79     13850986.75      3195461.67     13850949.16
      3195067.22     13850927.55      3194780.84     13850916.74
BEGIN DESCRIPTION:
Downstream Section of Bridge/Culvert/Weir
END DESCRIPTION:
#Sta/Elev= 30
    4147   22.72  4189.3    22.6  4344.5   22.15  4654.5   19.94  4694.5   20.88
  4734.5   19.31 4747.39    20.7 4776.75   19.87 4819.96   19.43 4823.68   18.86
 4826.02   19.77 4886.38    19.1 4918.16   19.95 4933.32   19.75 4940.85   20.47
 4950.64   19.94 4978.44   20.12 4983.55   19.32 4993.25    9.83 4995.58   10.02
 4997.14    8.22 5004.42    9.25 5006.84   10.06 5009.77   12.17 5029.53   18.89
 5043.91   19.91 5078.81   19.59  5210.4   20.65  5308.7   21.95  5465.8   24.88
#Mann= 5 , 1 , 0
 4147.00     0.2       0  4189.3     0.1       0 4983.55    0.04       0
 5029.53     0.1       0  5210.4     0.2       0
#XS Ineff= 2 , 0
       0    4979      20    5029       0      21
Bank Sta=4983.55,5029.53
Exp/Cntr=0.5,0.3

Type RM Length L Ch R = 1 ,5135.3,354.9,336.3,326.3
XS GIS Cut Line= 5
      3196098.65     13850987.65      3195640.37     13850961.46
      3195512.06     13850901.23      3195328.75     13850731.01
      3194949.03     13850477.00
BEGIN DESCRIPTION:
Cross Section 5135.3 - Interpolated
END DESCRIPTION:
#Sta/Elev= 30
  4235.1    23.3  4350.1    22.6  4380.1    21.4  4435.1    22.4  4505.1    21.5
  4520.1    21.9  4565.1    20.4  4620.1    20.2  4650.1    20.9  4694.1    20.2
  4729.1      21  4814.1    20.8  4835.9    19.9  4870.9    19.6  4935.9    20.4
  4960.9    19.3  4970.9      17  4985.9    12.8 4997.14    7.84 5004.42    8.87
 5006.84    9.68 5009.87   11.79 5029.53   18.51  5030.9    20.6    5086    21.7
  5210.4   22.18    5256    22.1    5346    23.2    5381    24.5  5542.9    26.1
#Mann= 4 , 1 , 0
 4235.10     0.1       0  4970.9    0.04       0 5029.53     0.1       0
  5210.4     0.2       0
Bank Sta=4970.90,5029.53
Exp/Cntr=0.3,0.1

Type RM Length L Ch R = 1 ,4799.0,263.7,240.9,219.4
XS GIS Cut Line= 4
      3196326.78     13850988.28      3195932.33     13850804.56
      3195600.02     13850580.32      3195168.65     13850493.66
BEGIN DESCRIPTION:
Cross Section 4799 - Interpolated
END DESCRIPTION:
#Sta/Elev= 28
  4265.1   24.57  4655.1   21.37  4665.1   21.75  4675.1   22.77  4695.1   23.53
  4700.2   23.45  4770.2   20.94  4800.2    20.9  4850.2   19.74  4880.2    20.3
  4960.2   18.42  4970.2   17.73  4979.7    15.6  4987.8    7.24  4997.1     7.5
  5020.3   16.54  5030.2   17.63  5040.2   18.52  5060.2   19.03  5090.2    21.3
  5100.2    21.1  5101.1   21.02  5121.1   19.66  5337.5   21.79  5461.1      23
  5491.1   25.25  5521.1   23.27  5541.1   23.62
#Mann= 5 , 1 , 0
 4265.10     0.2       0  4265.1     0.1       0  4979.7    0.04       0
  5020.3     0.1       0  5337.5     0.2       0
Bank Sta=4979.70,5020.30
Exp/Cntr=0.3,0.1