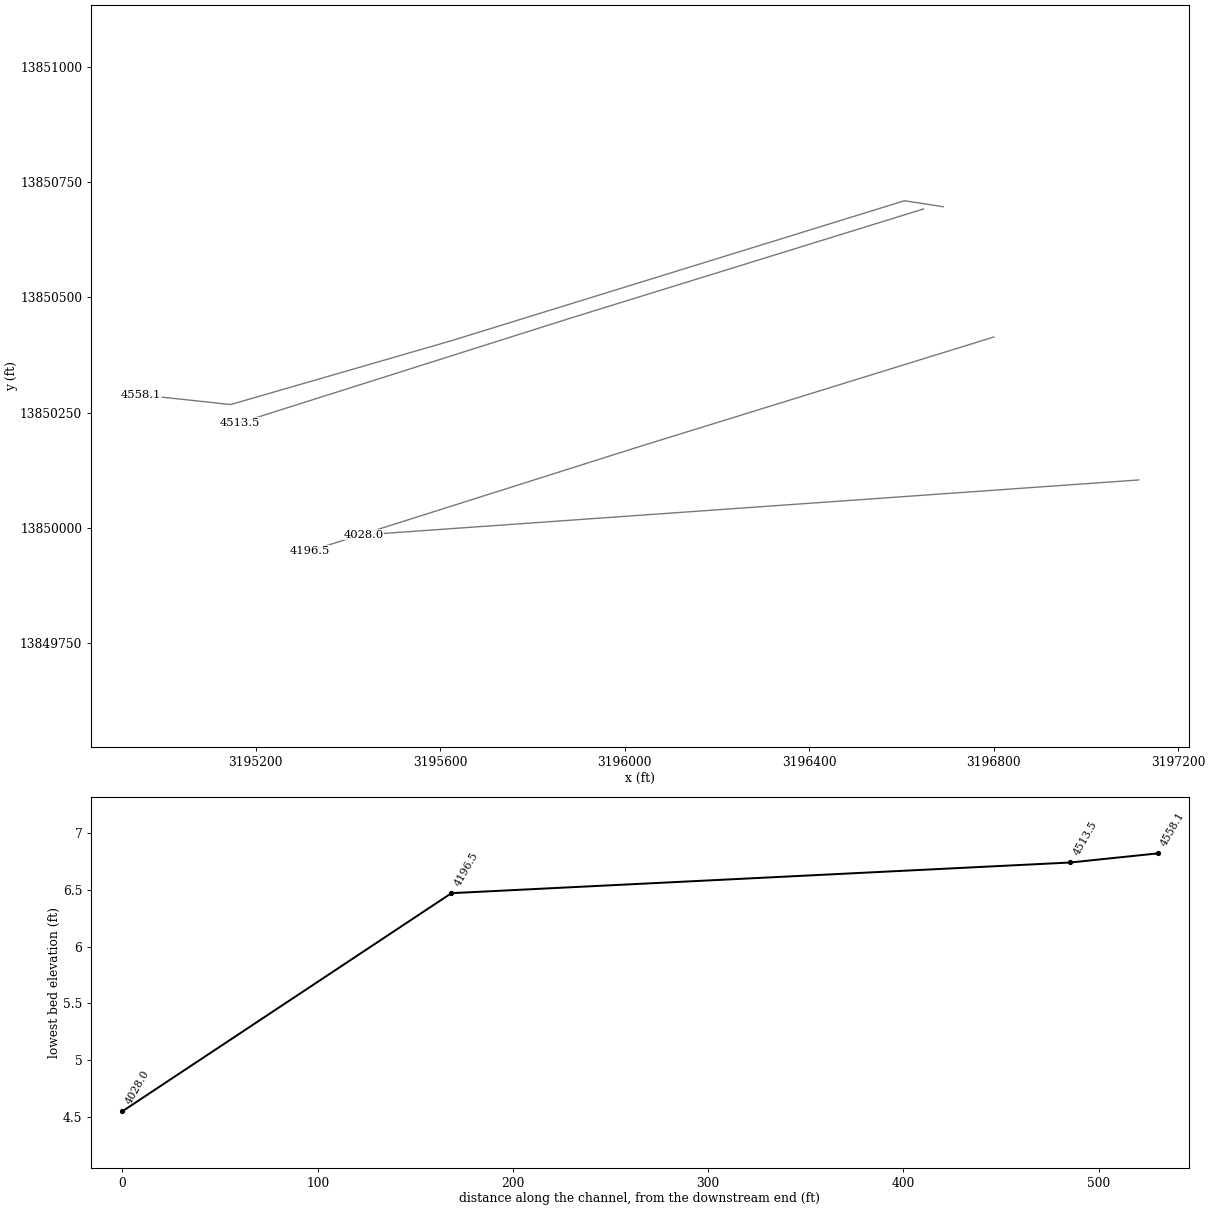
HEC-RAS study N104-00-00.PRJ: N104-00-00

--- N104-00-00.g01 (geometry) --- (continued)

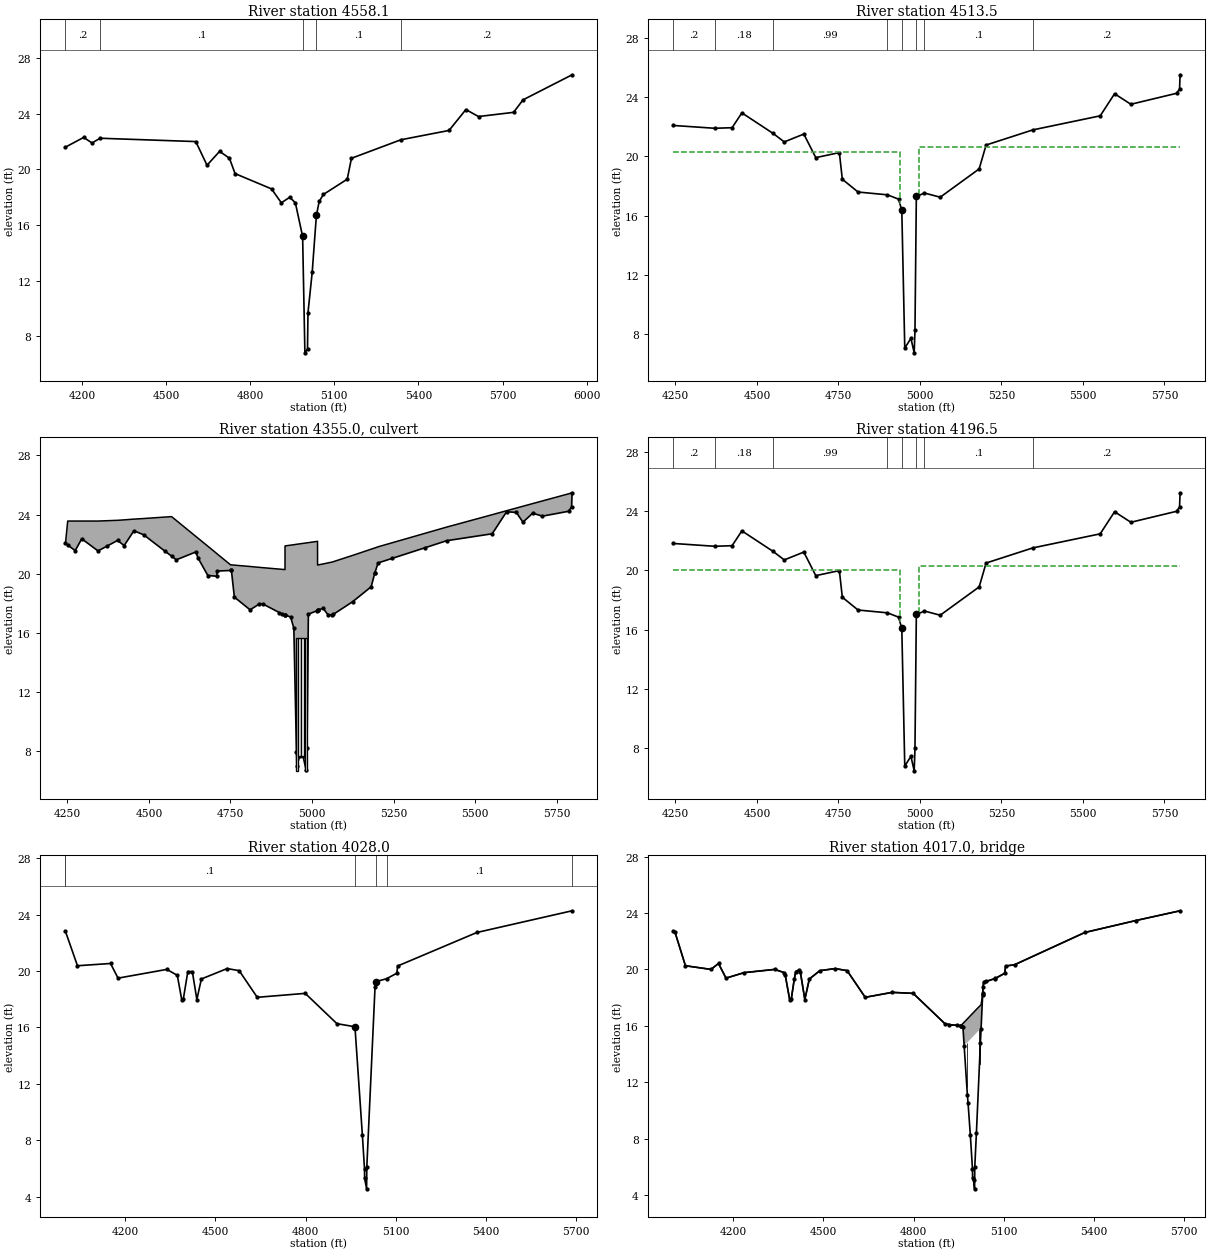
Type RM Length L Ch R = 1 ,4558.1,45.9,44.6,42.2
XS GIS Cut Line= 5
      3196690.49     13850696.97      3196606.69     13850710.06
      3195624.66     13850406.29      3195145.43     13850267.50
      3194951.65     13850288.45
BEGIN DESCRIPTION:
Cross Section 4558.1 - Interpolated
END DESCRIPTION:
#Sta/Elev= 30
  4141.5    21.6  4206.5    22.3  4236.3    21.9  4265.1   22.24  4606.3      22
  4646.3    20.3  4691.3    21.3  4726.3    20.8  4746.3    19.7  4876.3    18.6
  4911.3    17.6  4941.3      18  4961.3    17.6  4987.2   15.18  4995.3    6.82
  5004.6    7.08  5006.3     9.7  5021.3    12.6  5036.3    16.7  5046.3    17.7
  5061.3    18.2  5146.3    19.3  5161.3    20.8  5337.5   22.13  5509.3    22.8
  5569.3    24.3  5614.3    23.8  5739.3    24.1  5773.2      25  5948.1    26.8
#Mann= 5 , 1 , 0
 4141.50     0.2       0  4265.1     0.1       0  4987.2    0.04       0
  5036.3     0.1       0  5337.5     0.2       0
Bank Sta=4987.20,5036.30
Exp/Cntr=0.5,0.3

Type RM Length L Ch R = 1 ,4513.5,317,317,317
XS GIS Cut Line= 3
      3196647.92     13850692.18      3195880.52     13850454.57
      3195164.56     13850227.63
BEGIN DESCRIPTION:
Upstream Section of Bridge/Culvert/Weir
END DESCRIPTION:
#Sta/Elev= 30
  4243.8   22.08  4370.8   21.89  4423.8   21.93  4453.8   22.93  4549.8   21.54
  4583.8   20.97  4643.8    21.5  4680.5   19.91  4752.8   20.25  4761.9   18.45
  4810.1   17.59  4900.3    17.4  4934.3   17.11  4944.3   16.35  4953.4    7.06
  4972.3    7.72  4982.3    6.74  4984.7    8.25  4988.9   17.29  5013.9   17.52
  5062.1   17.24  5181.6   19.15  5202.8   20.76    5346   21.78  5552.8   22.73
  5596.9   24.22  5646.9   23.51  5786.9   24.25  5796.2   24.54  5797.8    25.5
#Mann= 8 , 1 , 0
 4243.80     0.2       0  4370.8    0.18       0  4549.8    0.99       0
  4900.3     0.1       0  4944.3   0.015       0  4988.9     0.1       0
  5013.9     0.1       0    5346     0.2       0
#XS Ineff= 2 , 0
       0    4939    20.3    4996       0    20.6
Bank Sta=4944.30,4988.90
Exp/Cntr=0.5,0.3

Type RM Length L Ch R = 2 ,4355.0,,,
BEGIN DESCRIPTION:
INTERSTATE 10
Structure ID: N04-5
END DESCRIPTION:
Bridge Culvert--1,0,-1,-1, 0
Deck Dist Width WeirC Skew NumUp NumDn MinLoCord MaxHiCord MaxSubmerge Is_Ogee
10,297,3,, 52, 52,,,0.95,0,1,1,,
  4243.8  4250.8  4273.8  4293.8  4343.8  4403.8  4423.8  4453.8  4483.8  4569.3
  4583.8  4643.8  4650.5  4680.5  4708.2  4708.5  4750.3  4752.8  4761.9  4810.1
  4838.8  4848.9 4917.19  4917.3  4934.3  4944.3  4952.4  4953.4  4962.6  4972.3
  4982.3  4984.7  4988.9    5017 5017.11  5033.9  5048.8  5062.1  5124.8  5181.6
  5192.5  5202.8  5412.8  5552.8  5596.9  5626.9  5646.9  5676.9  5706.9  5786.9
  5796.2  5797.8
   22.06   23.57   23.57   23.57   23.57   23.62   23.65    23.7   23.74   23.87
   23.61   22.53   22.41   21.87   21.37   21.36   20.61   20.61   20.59    20.5
   20.44   20.42   20.29   21.89   21.94   21.97      22      22   22.03   22.06
   22.09    22.1   22.11    22.2    20.6   20.67   20.74    20.8   21.25   21.67
   21.75   21.83   23.16      24   24.27   24.45   24.57   24.75   24.93   25.41
   25.47   25.48
   22.06   21.95   21.57   22.37   21.55   22.26   21.91   22.91   22.64    21.2
   20.95   21.48   21.07   19.89   19.84   20.19   20.23   20.23   18.43   17.57
   17.97   17.97   17.22   17.22   17.09   16.33    7.97    7.04     7.7     7.7
    6.72    8.23   17.27   17.53   17.53   17.68   17.24   17.22   18.12   19.13
   20.05   20.74   22.24   22.71    24.2   24.15   23.49    24.1    23.9   24.23
   24.52   25.48
  4243.8  4250.8  4273.8  4293.8  4343.8  4403.8  4423.8  4453.8  4483.8  4569.3
  4583.8  4643.8  4650.5  4680.5  4708.2  4708.5  4750.3  4752.8  4761.9  4810.1
  4838.8  4848.9 4917.19  4917.3  4934.3  4944.3  4952.4  4953.4  4962.6  4972.3
  4982.3  4984.7  4988.9    5017 5017.11  5033.9  5048.8  5062.1  5124.8  5181.6
  5192.5  5202.8  5412.8  5552.8  5596.9  5626.9  5646.9  5676.9  5706.9  5786.9
  5796.2  5797.8
   22.06   23.57   23.57   23.57   23.57   23.62   23.65    23.7   23.74   23.87
   23.61   22.53   22.41   21.87   21.37   21.36   20.61   20.61   20.59    20.5
   20.44   20.42   20.29   21.89   21.94   21.97      22      22   22.03   22.06
   22.09    22.1   22.11    22.2    20.6   20.67   20.74    20.8   21.25   21.67
   21.75   21.83   23.16      24   24.27   24.45   24.57   24.75   24.93   25.41
   25.47   25.48
   21.92   21.81   21.43   22.23   21.41   22.12   21.77   22.77    22.5   21.06
   20.81   21.34   20.93   19.75    19.7   20.05   20.09   20.09   18.29   17.43
   17.83   17.83   17.08   17.08   16.95   16.19    7.83     6.9    7.56    7.56
    6.58    8.09   17.13   17.39   17.39   17.54    17.1   17.08   17.98   18.99
   19.91    20.6    22.1   22.57   24.06   24.01   23.35   23.96   23.76   24.09
   24.38   25.34
BR Coef= 1 , 0 , 0 ,1.25, 0 ,,,0.8,-1,2,0,
Wspro=,,,, 1 ,,,, 0 ,,,, 0 ,,,,-1 ,-1 ,-1 , 0 , 0 , 0 , 0 , 0
Culvert=2,9.0,8.0,297.0,0.015,0.2,1.0,8,1,6.69,4953.60,5.95,4953.60,Culvert #1  ,0,10
Culvert=2,8.0,8.3,297.0,0.015,0.2,1.0,8,1,7.67,4962.60,6.92,4962.60,Culvert #2  ,0,10
Culvert=2,8.0,8.4,297.0,0.015,0.2,1.0,8,1,7.69,4971.80,6.95,4971.80,Culvert #3  ,0,10
Culvert=2,9.0,8.0,297.0,0.015,0.2,1.0,8,1,6.69,4981.60,5.95,4981.60,Culvert #4  ,0,10
BC Design=,, 0 ,, 0 ,,,,,,
BR U #Sta/Elev= 63
  4243.8   22.06  4250.8   21.95  4273.8   21.57  4293.8   22.37  4343.8   21.55
  4370.8   21.87  4403.8   22.26  4423.8   21.91  4453.8   22.91  4483.8   22.64
  4549.8   21.52  4569.3    21.2  4583.8   20.95  4643.8   21.48  4650.5   21.07
  4680.5   19.89  4708.2   19.84  4708.5   20.19  4750.3   20.23  4752.8   20.23
  4761.9   18.43  4810.1   17.57  4838.8   17.97  4848.9   17.97  4900.3   17.38
  4908.4   17.29 4917.19   17.22  4917.3   17.22 4917.41   17.22  4934.3   17.09
  4944.3   16.33  4952.4    7.97  4953.4    7.04  4962.6     7.7  4972.3     7.7
  4982.3    6.72  4984.7    8.23  4988.9   17.27  5013.9    17.5 5016.89   17.53
    5017   17.53 5017.11   17.53  5033.9   17.68  5048.8   17.24  5062.1   17.22
  5065.1   17.26  5124.8   18.12  5181.6   19.13  5192.5   20.05  5192.8   20.07
  5202.8   20.74  5246.2   21.05    5346   21.76  5412.8   22.24  5552.8   22.71
  5596.9    24.2  5626.9   24.15  5646.9   23.49  5676.9    24.1  5706.9    23.9
  5786.9   24.23  5796.2   24.52  5797.8   25.48
BR U #Mann= 8
 4243.80     0.2  4370.8    0.18  4549.8    0.99  4900.3     0.1  4944.3   0.015
  4988.9     0.1  5013.9     0.1    5346     0.2
BR U Banks=4944.30,4988.90
BR D #Sta/Elev= 63
  4243.8   21.92  4250.8   21.81  4273.8   21.43  4293.8   22.23  4343.8   21.41
  4370.8   21.73  4403.8   22.12  4423.8   21.77  4453.8   22.77  4483.8    22.5
  4549.8   21.38  4569.3   21.06  4583.8   20.81  4643.8   21.34  4650.5   20.93
  4680.5   19.75  4708.2    19.7  4708.5   20.05  4750.3   20.09  4752.8   20.09
  4761.9   18.29  4810.1   17.43  4838.8   17.83  4848.9   17.83  4900.3   17.24
  4908.4   17.15 4917.19   17.08  4917.3   17.08 4917.41   17.08  4934.3   16.95
  4944.3   16.19  4952.4    7.83  4953.4     6.9  4962.6    7.56  4972.3    7.56
  4982.3    6.58  4984.7    8.09  4988.9   17.13  5013.9   17.36 5016.89   17.39
    5017   17.39 5017.11   17.39  5033.9   17.54  5048.8    17.1  5062.1   17.08
  5065.1   17.12  5124.8   17.98  5181.6   18.99  5192.5   19.91  5192.8   19.93
  5202.8    20.6  5246.2   20.91    5346   21.62  5412.8    22.1  5552.8   22.57
  5596.9   24.06  5626.9   24.01  5646.9   23.35  5676.9   23.96  5706.9   23.76
  5786.9   24.09  5796.2   24.38  5797.8   25.34
BR D #Mann= 8
 4243.80     0.2  4370.8    0.18  4549.8    0.99  4900.3     0.1  4944.3   0.015
  4988.9     0.1  5013.9     0.1    5346     0.2
BR D Banks=4944.30,4988.90

Type RM Length L Ch R = 1 ,4196.5,168.5,168.5,168.5
XS GIS Cut Line= 3
      3196800.19     13850414.14      3196032.78     13850176.53
      3195316.82     13849949.59
BEGIN DESCRIPTION:
Downstream Section of Bridge/Culvert/Weir
END DESCRIPTION:
#Sta/Elev= 30
  4243.8   21.81  4370.8   21.62  4423.8   21.66  4453.8   22.66  4549.8   21.27
  4583.8    20.7  4643.8   21.23  4680.5   19.64  4752.8   19.98  4761.9   18.18
  4810.1   17.32  4900.3   17.13  4934.3   16.84  4944.3   16.08  4953.4    6.79
  4972.3    7.45  4982.3    6.47  4984.7    7.98  4988.9   17.02  5013.9   17.25
  5062.1   16.97  5181.6   18.88  5202.8   20.49    5346   21.51  5552.8   22.46
  5596.9   23.95  5646.9   23.24  5786.9   23.98  5796.2   24.27  5797.8   25.23
#Mann= 8 , 1 , 0
 4243.80     0.2       0  4370.8    0.18       0  4549.8    0.99       0
  4900.3     0.1       0  4944.3   0.015       0  4988.9     0.1       0
  5013.9     0.1       0    5346     0.2       0
#XS Ineff= 2 , 0
       0    4939      20    4996       0    20.3
Bank Sta=4944.30,4988.90
Exp/Cntr=0.5,0.3

Type RM Length L Ch R = 1 ,4028.0,22,22,22
XS GIS Cut Line= 2
      3197114.47     13850103.81      3195433.49     13849984.59
BEGIN DESCRIPTION:
Upstream Section of Bridge/Culvert/Weir
END DESCRIPTION:
#Sta/Elev= 30
  4001.4   22.82  4041.4   20.38  4151.4   20.54  4176.4    19.5  4338.5   20.12
  4373.5    19.7  4388.5   17.93  4393.5   18.02  4408.5   19.97  4423.5   19.96
  4438.5   17.98  4453.5   19.44  4539.3   20.18  4579.3   20.03  4639.3   18.14
  4798.9   18.42 4904.35   16.27 4964.35   16.05 4989.05    8.35 4996.15    5.95
 4996.45     5.3 5003.05    4.55 5003.75    6.09 5031.05   18.85 5033.75   19.25
  5069.5   19.46 5103.75   19.85  5106.1   20.36  5369.9   22.74  5686.6   24.28
#Mann= 6 , 1 , 0
 4001.40     0.2       0  4001.4     0.1       0 4964.35    0.04       0
 5033.75    0.08       0  5069.5     0.1       0  5686.6     0.2       0
#XS Ineff= 2 , 0
       0  4966.3    15.2  5026.4       0    16.6
Bank Sta=4964.35,5033.75
Exp/Cntr=0.5,0.3

Type RM Length L Ch R = 3 ,4017.0,,,
BEGIN DESCRIPTION:
24" PIPELINE
END DESCRIPTION:
Bridge Culvert--1,0,-1,-1, 0
Deck Dist Width WeirC Skew NumUp NumDn MinLoCord MaxHiCord MaxSubmerge Is_Ogee
10,2,2.6,,57,57,,,0.95,0,1,1,,
  4001.4  4006.4  4041.4  4126.4  4151.4  4176.4  4236.4  4338.5  4368.5  4373.5
  4388.5  4393.5  4403.5  4408.5  4418.5  4423.5  4438.5  4453.5  4488.5  4539.3
  4579.3  4639.3  4728.9  4798.9 4904.35 4919.35 4944.85 4959.35 4959.46 4959.55
 4964.35 4968.35 4979.25 4981.45 4989.05 4996.15 4996.45 4999.75 5003.05 5003.75
 5009.15 5022.45 5024.75 5029.94 5030.05 5030.15 5031.05 5033.75 5042.05  5069.5
 5072.05 5103.75  5106.1  5136.1  5369.9  5539.9  5686.6
    22.7   22.66   20.26      20   20.42   19.38   19.77      20   19.78   19.58
   17.81    17.9   19.32   19.85   19.95   19.84   17.86   19.32   19.91   20.06
   19.91   18.02   18.37    18.3   16.15   16.08   16.03   16.05   16.05   16.05
   16.16   16.25   16.49   16.54   16.71   16.87   16.87   16.95   17.02   17.04
   17.16   17.45    17.5   18.22   18.27   18.31   18.73   19.13   19.15   19.34
   19.36   19.73   20.24   20.33   22.62   23.47   24.16
    22.7   22.66   20.26      20   20.42   19.38   19.77      20   19.78   19.58
   17.81    17.9   19.32   19.85   19.95   19.84   17.86   19.32   19.91   20.06
   19.91   18.02   18.37    18.3   16.15   16.08   16.03   15.96   15.96   15.95
   15.93    14.6   14.82   14.87   15.04    15.2    15.2   15.28   15.35   15.37
   15.49   15.78   15.83   18.21   18.26   18.31   18.73   19.13   19.15   19.34
   19.36   19.73   20.24   20.33   22.62   23.47   24.16
  4001.4  4006.4  4041.4  4126.4  4151.4  4176.4  4236.4  4338.5  4368.5  4373.5
  4388.5  4393.5  4403.5  4408.5  4418.5  4423.5  4438.5  4453.5  4488.5  4539.3
  4579.3  4639.3  4728.9  4798.9 4904.35 4919.35 4944.85 4959.35 4959.46 4959.55
 4964.35 4968.35 4979.25 4981.45 4989.05 4996.15 4996.45 4999.75 5003.05 5003.75
 5009.15 5022.45 5024.75 5029.94 5030.05 5030.15 5031.05 5033.75 5042.05  5069.5
 5072.05 5103.75  5106.1  5136.1  5369.9  5539.9  5686.6
    22.7   22.66   20.26      20   20.42   19.38   19.77      20   19.78   19.58
   17.81    17.9   19.32   19.85   19.95   19.84   17.86   19.32   19.91   20.06
   19.91   18.02   18.37    18.3   16.15   16.08   16.03   16.05   16.05   16.05
   16.16   16.25   16.49   16.54   16.71   16.87   16.87   16.95   17.02   17.04
   17.16   17.45    17.5   18.22   18.27   18.31   18.73   19.13   19.15   19.34
   19.36   19.73   20.24   20.33   22.62   23.47   24.16
    22.7   22.66   20.26      20   20.42   19.38   19.77      20   19.78   19.58
   17.81    17.9   19.32   19.85   19.95   19.84   17.86   19.32   19.91   20.06
   19.91   18.02   18.37    18.3   16.15   16.08   16.03   15.96   15.96   15.95
   15.93    14.6   14.82   14.87   15.04    15.2    15.2   15.28   15.35   15.37
   15.49   15.78   15.83   18.21   18.26   18.31   18.73   19.13   19.15   19.34
   19.36   19.73   20.24   20.33   22.62   23.47   24.16
Pier Skew, UpSta & Num, DnSta & Num=,4977.5, 2 ,4977.5, 2 , 0 , 0 , 0 ,,
     1.5     1.5
   10.41    15.8
     1.5     1.5
   10.41    15.8
Pier Skew, UpSta & Num, DnSta & Num=,5019.4, 2 ,5019.4, 2 , 0 , 0 , 0 ,,
     1.5     1.5
   11.93   16.73
     1.5     1.5
   11.93   16.73
BR Coef= 1 , 1 , 0 ,1.25, 0 ,,,0.8,0,2,0,
Wspro=,,,, 1 ,,,, 0 ,,,, 0 ,,,,-1 ,-1 ,-1 , 0 , 0 , 0 , 0 , 0
BC Design=,, 0 ,, 0 ,,,,,,
BR U #Sta/Elev= 57
  4001.4    22.7  4006.4   22.66  4041.4   20.26  4126.4      20  4151.4   20.42
  4176.4   19.38  4236.4   19.77  4338.5      20  4368.5   19.78  4373.5   19.58
  4388.5   17.81  4393.5    17.9  4403.5   19.32  4408.5   19.85  4418.5   19.95
  4423.5   19.84  4438.5   17.86  4453.5   19.32  4488.5   19.91  4539.3   20.06
  4579.3   19.91  4639.3   18.02  4728.9   18.37  4798.9    18.3 4904.35   16.15
 4919.35   16.08 4944.85   16.03 4959.35   15.96 4959.46   15.96 4959.55   15.95
 4964.35   15.93 4968.35    14.6 4979.25   11.07 4981.45   10.51 4989.05    8.23
 4996.15    5.83 4996.45    5.18 4999.75    5.04 5003.05    4.43 5003.75    5.97
 5009.15    8.38 5022.45   14.78 5024.75    15.8 5029.94   18.21 5030.05   18.26
 5030.15   18.31 5031.05   18.73 5033.75   19.13 5042.05   19.15  5069.5   19.34
 5072.05   19.36 5103.75   19.73  5106.1   20.24  5136.1   20.33  5369.9   22.62
  5539.9   23.47  5686.6   24.16
BR U #Mann= 6
 4001.40     0.2  4001.4     0.1 4964.35    0.04 5033.75    0.08  5069.5     0.1
  5686.6     0.2
BR U Banks=4964.35,5033.75
BR D #Sta/Elev= 57
  4001.4    22.7  4006.4   22.66  4041.4   20.26  4126.4      20  4151.4   20.42
  4176.4   19.38  4236.4   19.77  4338.5      20  4368.5   19.78  4373.5   19.58
  4388.5   17.81  4393.5    17.9  4403.5   19.32  4408.5   19.85  4418.5   19.95
  4423.5   19.84  4438.5   17.86  4453.5   19.32  4488.5   19.91  4539.3   20.06
  4579.3   19.91  4639.3   18.02  4728.9   18.37  4798.9    18.3 4904.35   16.15
 4919.35   16.08 4944.85   16.03 4959.35   15.96 4959.46   15.96 4959.55   15.95
 4964.35   15.93 4968.35    14.6 4979.25   11.07 4981.45   10.51 4989.05    8.23
 4996.15    5.83 4996.45    5.18 4999.75    5.04 5003.05    4.43 5003.75    5.97
 5009.15    8.38 5022.45   14.78 5024.75    15.8 5029.94   18.21 5030.05   18.26
 5030.15   18.31 5031.05   18.73 5033.75   19.13 5042.05   19.15  5069.5   19.34
 5072.05   19.36 5103.75   19.73  5106.1   20.24  5136.1   20.33  5369.9   22.62
  5539.9   23.47  5686.6   24.16
BR D #Mann= 6
 4001.40     0.2  4001.4     0.1 4964.35    0.04 5033.75    0.08  5069.5     0.1
  5686.6     0.2
BR D Banks=4964.35,5033.75