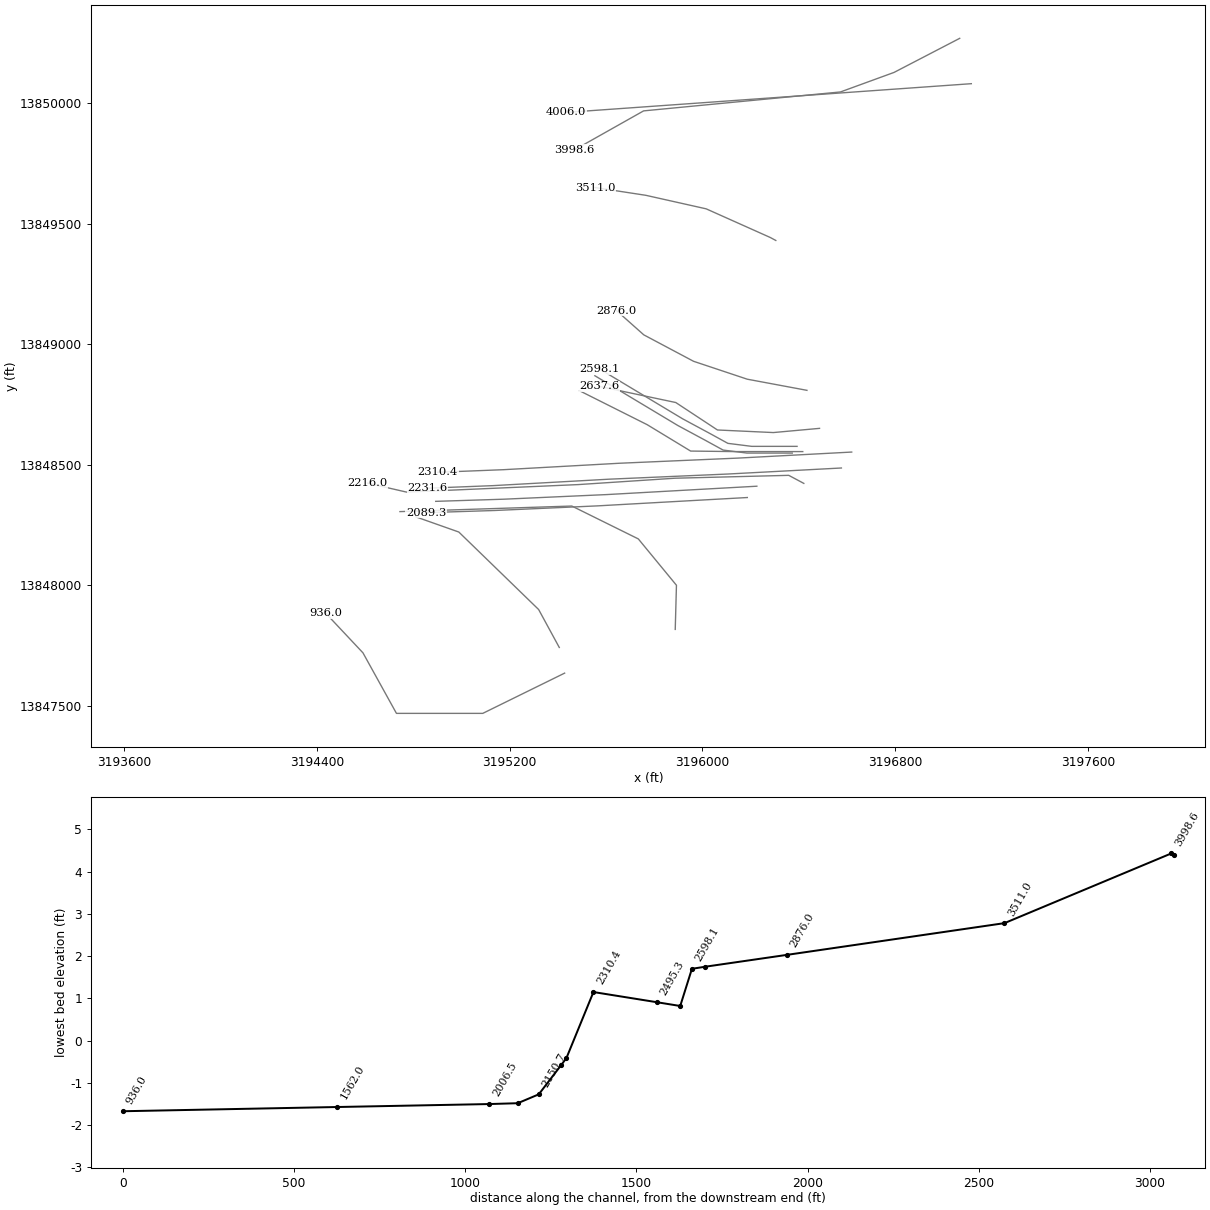
HEC-RAS study N104-00-00.PRJ: N104-00-00

--- N104-00-00.g01 (geometry) --- (continued)

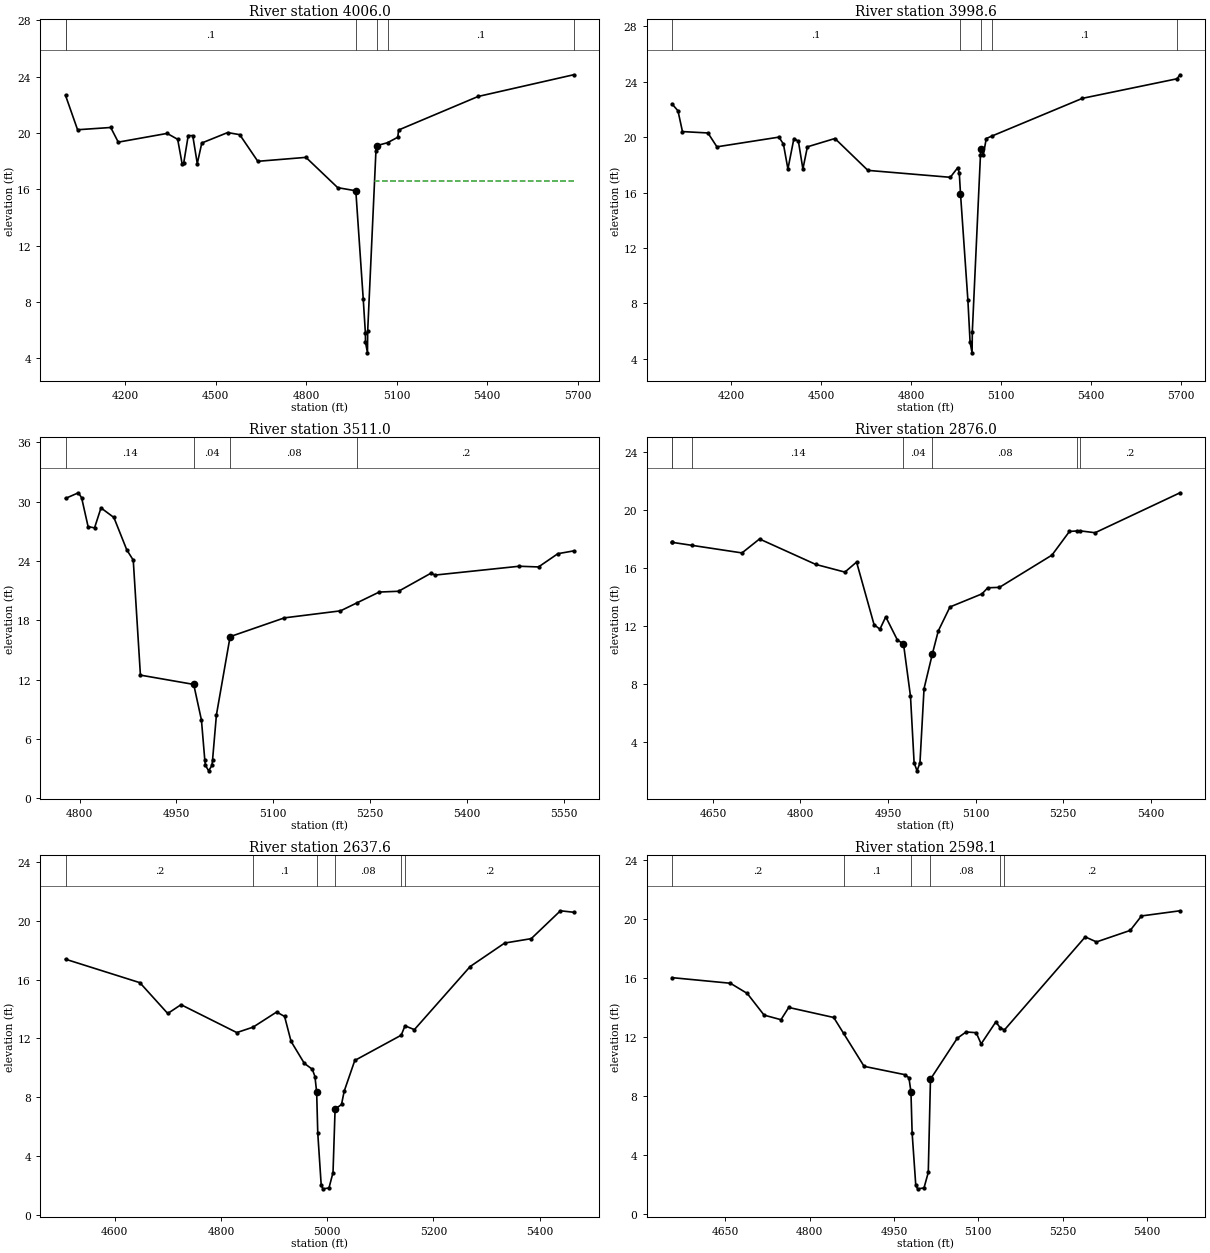
Type RM Length L Ch R = 1 ,4006.0,7.4,7.4,7.4
XS GIS Cut Line= 2
      3197115.80     13850081.85      3195434.82     13849962.63
BEGIN DESCRIPTION:
Downstream Section of Bridge/Culvert/Weir
END DESCRIPTION:
#Sta/Elev= 30
  4001.4   22.67  4041.4   20.23  4151.4   20.39  4176.4   19.35  4338.5   19.97
  4373.5   19.55  4388.5   17.78  4393.5   17.87  4408.5   19.82  4423.5   19.81
  4438.5   17.83  4453.5   19.29  4539.3   20.03  4579.3   19.88  4639.3   17.99
  4798.9   18.27 4904.35   16.12 4964.35    15.9 4989.05     8.2 4996.15     5.8
 4996.45    5.15 5003.05     4.4 5003.75    5.94 5031.05    18.7 5033.75    19.1
  5069.5   19.31 5103.75    19.7  5106.1   20.21  5369.9   22.59  5686.6   24.13
#Mann= 6 , 1 , 0
 4001.40     0.2       0  4001.4     0.1       0 4964.35    0.04       0
 5033.75    0.08       0  5069.5     0.1       0  5686.6     0.2       0
#XS Ineff= 2 , 0
       0  4966.3    15.2  5026.4       0    16.6
Bank Sta=4964.35,5033.75
Exp/Cntr=0.5,0.3

Type RM Length L Ch R = 1 ,3998.6,519.8,487.6,467.8
XS GIS Cut Line= 5
      3197067.58     13850270.12      3196795.23     13850128.71
      3196572.64     13850047.53      3195755.60     13849968.96
      3195467.54     13849806.60
BEGIN DESCRIPTION:
Cross Section 3998.6 - Interpolated
END DESCRIPTION:
#Sta/Elev= 30
  4001.6    22.4  4021.6    21.9  4036.6    20.4  4121.6    20.3  4151.6    19.3
  4358.5      20  4373.5    19.5  4388.5    17.7  4408.5    19.9  4423.5    19.7
  4438.5    17.7  4453.5    19.3  4545.4    19.9  4655.4    17.6  4930.4    17.1
  4955.4    17.8  4960.4    17.4 4964.35   15.93 4989.05    8.23 4996.45    5.18
 5003.05    4.43 5003.85    5.97 5031.05   18.73 5033.75   19.13  5040.4    18.7
  5050.4    19.9  5069.5   20.08  5371.2    22.8  5686.6   24.21  5696.9    24.5
#Mann= 5 , 1 , 0
 4001.60     0.1       0 4964.35    0.04       0 5033.75    0.08       0
  5069.5     0.1       0  5686.6     0.2       0
Bank Sta=4964.35,5033.75
Exp/Cntr=0.3,0.1

Type RM Length L Ch R = 1 ,3511.0,625.1,635,633.6
XS GIS Cut Line= 5
      3196304.29     13849431.00      3196281.12     13849443.44
      3196015.27     13849562.31      3195764.55     13849618.51
      3195554.06     13849650.73
BEGIN DESCRIPTION:
Cross Section 3511.0
Located At: 1ST XS US MARKET
END DESCRIPTION:
#Sta/Elev= 30
  4778.1   30.33  4798.1    30.9  4803.1   30.39  4813.1   27.48  4823.1   27.35
  4833.1   29.37  4853.1    28.4  4873.1   25.12  4883.1   24.09  4894.2   12.46
  4976.8   11.52  4988.8    7.91    4994    3.86    4995    3.33    5000    2.78
    5005    3.32    5006    3.87    5012    8.44  5033.2   16.35  5117.3   18.25
  5204.3   18.96  5230.5   19.79  5264.3   20.86  5294.3   20.94  5344.3   22.76
  5351.2   22.58  5481.2   23.47  5511.2    23.4  5541.2   24.74  5565.5   25.02
#Mann= 4 , 1 , 0
 4778.10    0.14       0  4976.8    0.04       0  5033.2    0.08       0
  5230.5     0.2       0
Bank Sta=4976.80,5033.20
Exp/Cntr=0.3,0.1

Type RM Length L Ch R = 1 ,2876.0,243.7,238.4,202.7
XS GIS Cut Line= 5
      3196433.50     13848808.86      3196185.73     13848855.11
      3195963.00     13848929.35      3195756.41     13849039.11
      3195644.50     13849138.59
BEGIN DESCRIPTION:
Cross Section 2876 - Interpolated
END DESCRIPTION:
#Sta/Elev= 30
  4579.9   17.76    4580   17.76  4614.4   17.55  4699.9   17.03  4729.9   17.99
  4826.2   16.24  4876.2   15.71  4896.2    16.4  4926.2   12.09  4936.2   11.78
  4946.2   12.63  4966.2   11.03  4976.6   10.77  4988.6    7.16  4994.8    2.58
  4999.8    2.03  5004.8    2.57  5011.8    7.69  5026.2    10.1  5036.2   11.66
  5056.2   13.31    5111   14.21    5121   14.63    5141   14.66    5231   16.88
    5261   18.51  5273.3   18.54  5279.1   18.55  5304.9   18.42  5450.4   21.17
#Mann= 7 , 1 , 0
 4579.90     0.2       0    4580     0.1       0  4614.4    0.14       0
  4976.6    0.04       0  5026.2    0.08       0  5273.3    0.14       0
  5279.1     0.2       0
Bank Sta=4976.60,5026.20
Exp/Cntr=0.3,0.1

Type RM Length L Ch R = 1 ,2637.6,22,39.5,24.3
XS GIS Cut Line= 5
      3196485.76     13848650.98      3196294.03     13848633.55
      3196062.07     13848644.27      3195889.11     13848758.24
      3195571.34     13848825.28
BEGIN DESCRIPTION:
Cross Section 2637.6 - Interpolated
END DESCRIPTION:
#Sta/Elev= 30
  4507.4    17.4  4647.4    15.8  4699.9    13.7  4724.9    14.3  4829.9    12.4
  4860.6   12.77  4904.9    13.8  4919.9    13.5  4932.1    11.8  4957.1    10.3
  4972.1     9.9  4977.1     9.4  4980.3    8.33  4982.4    5.54  4988.9    1.98
  4992.2    1.75  5003.5    1.81  5011.1    2.86    5015    7.18  5027.1     7.5
  5032.1     8.4  5052.1    10.5  5139.5   12.22  5146.6   12.86  5164.3    12.6
  5269.3    16.9  5334.3    18.5  5384.3    18.8  5439.3    20.7    5464    20.6
#Mann= 6 , 1 , 0
 4507.40     0.2       0  4860.6     0.1       0  4980.3    0.04       0
    5015    0.08       0  5139.5    0.14       0  5146.6     0.2       0
Bank Sta=4980.30,5015.00
Exp/Cntr=0.5,0.3

Type RM Length L Ch R = 1 ,2598.1,34.2,34.2,34.2
XS GIS Cut Line= 6
      3196392.52     13848576.24      3196204.34     13848576.26
      3196105.47     13848588.71      3196030.17     13848629.98
      3195917.78     13848690.50      3195573.12     13848897.32
BEGIN DESCRIPTION:
Upstream Section of Bridge/Culvert/Weir
END DESCRIPTION:
#Sta/Elev= 30
  4555.4   16.01  4659.2   15.63  4689.2   14.94  4719.2   13.47  4749.2   13.16
    4763   13.99    4843   13.31  4860.6   12.23    4897      10  4968.9    9.44
  4976.7    9.23  4980.3    8.28  4982.4    5.49  4988.9    1.93  4992.2     1.7
  5003.5    1.76  5011.1    2.81    5015    9.13  5062.6    11.9  5078.3   12.33
  5096.3   12.28  5105.1   11.52  5131.2   13.01  5139.5   12.59  5146.6   12.47
  5290.2   18.77  5310.2   18.43  5370.2   19.21  5390.2   20.19  5458.7   20.54
#Mann= 6 , 1 , 0
 4555.40     0.2       0  4860.6     0.1       0  4980.3    0.04       0
    5015    0.08       0  5139.5    0.14       0  5146.6     0.2       0
#XS Ineff= 2 , 0
       0    4970     9.2    5024       0     9.2
Bank Sta=4980.30,5015.00
Exp/Cntr=0.5,0.3

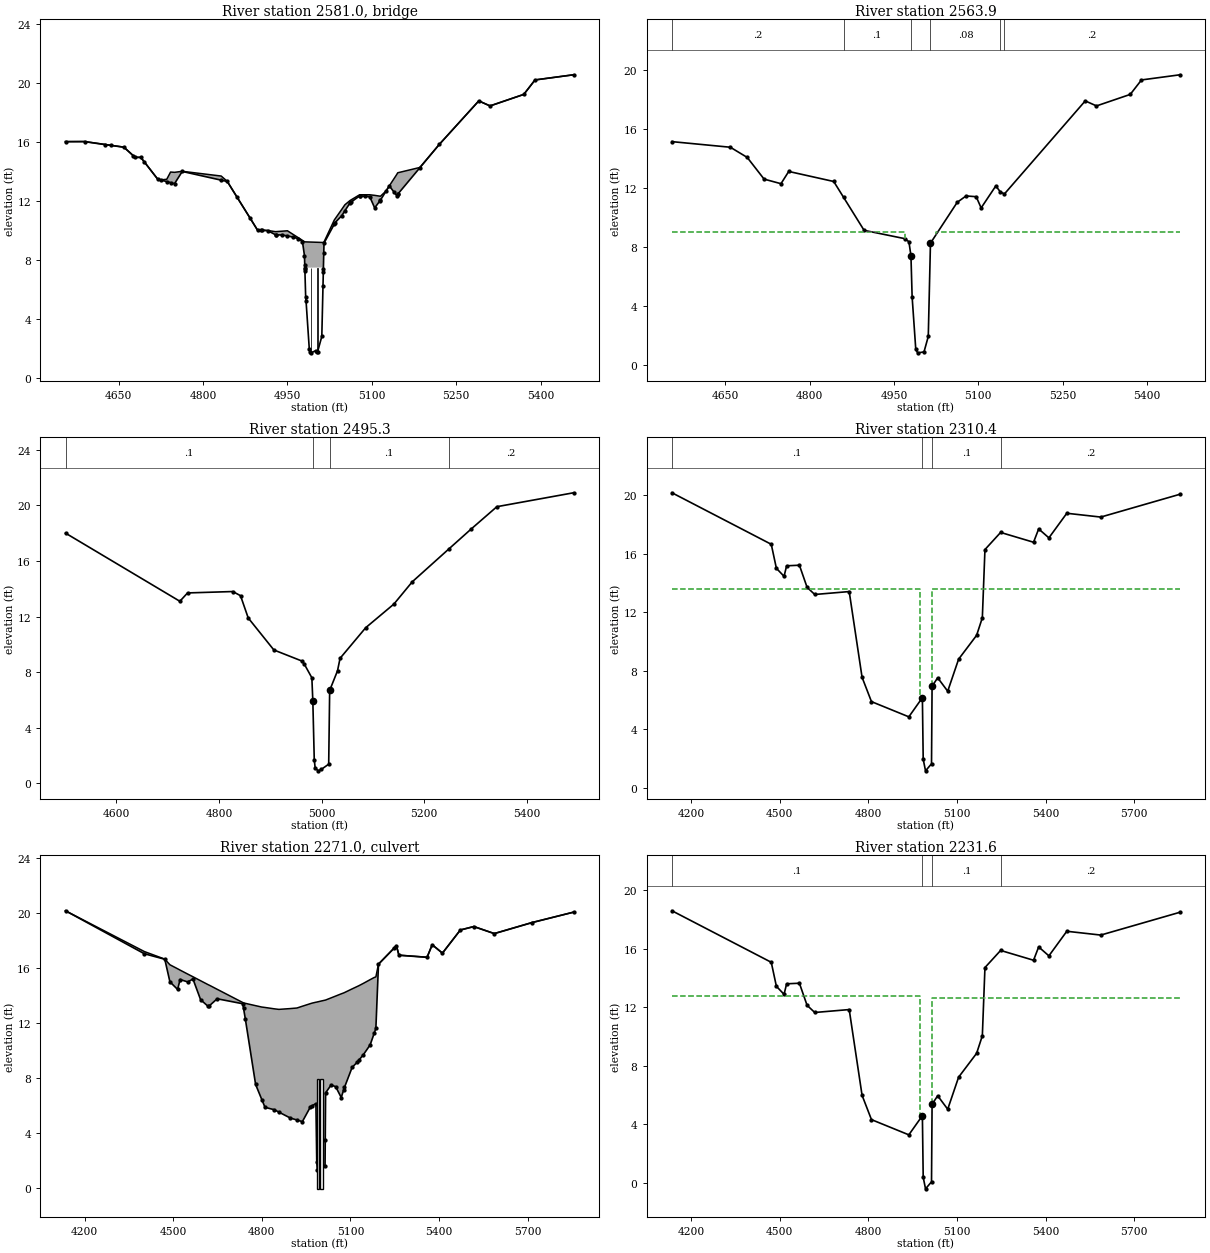
Type RM Length L Ch R = 3 ,2581.0,,,
BEGIN DESCRIPTION:
PRIVATE DRIVE
Structure ID: N04-3
END DESCRIPTION:
Bridge Culvert--1,0,-1,-1, 0
Deck Dist Width WeirC Skew NumUp NumDn MinLoCord MaxHiCord MaxSubmerge Is_Ogee
10,14.2,2.6,, 44, 44,,,0.95,0,1,1,,
  4555.4  4589.2  4659.2  4679.2  4689.2  4719.2  4725.4  4735.4  4742.2  4749.2
    4763  4832.2    4843    4897  4914.9  4928.8    4950  4968.9  4976.7  4980.3
 4980.91  5011.1 5013.79  5013.9    5015  5033.3  5046.7  5052.1  5061.3  5078.3
  5096.3  5105.1  5115.4  5125.4  5131.2  5144.1  5146.1  5185.4  5220.2  5290.2
  5310.2  5370.2  5390.2  5458.7
      16   16.01   15.63   14.94   14.94   13.47   13.41   13.45   13.94   13.92
   13.99   13.67   13.31      10    9.98     9.9    9.96     9.5    9.31    9.22
    9.21    9.17    9.17    9.17     9.2   10.69   11.42   11.72   12.01    12.4
    12.4   12.36    12.3   12.66   13.01   13.76   13.89   14.25   15.82   18.76
   18.42    19.2   20.18   20.53
      16      16   15.62   14.93   14.93   13.46    13.4   13.29   13.22   13.15
   13.98   13.39    13.3    9.99    9.97    9.69    9.61    9.43    9.22    8.27
    7.46    7.47    7.47    7.34    9.12   10.41   10.99   11.31   11.85   12.32
   12.27   11.51   12.04   12.65      13   12.35   12.44   14.23   15.82   18.76
   18.42    19.2   20.18   20.53
  4555.4  4589.2  4659.2  4679.2  4689.2  4719.2  4725.4  4735.4  4742.2  4749.2
    4763  4832.2    4843    4897  4914.9  4928.8    4950  4968.9  4976.7  4980.3
 4980.91  5011.1 5013.79  5013.9    5015  5033.3  5046.7  5052.1  5061.3  5078.3
  5096.3  5105.1  5115.4  5125.4  5131.2  5144.1  5146.1  5185.4  5220.2  5290.2
  5310.2  5370.2  5390.2  5458.7
      16   16.01   15.63   14.94   14.94   13.47   13.41   13.45   13.94   13.92
   13.99   13.67   13.31      10    9.98     9.9    9.96     9.5    9.31    9.22
    9.21    9.17    9.17    9.17     9.2   10.69   11.42   11.72   12.01    12.4
    12.4   12.36    12.3   12.66   13.01   13.76   13.89   14.25   15.82   18.76
   18.42    19.2   20.18   20.53
   15.14   15.14   14.76   14.07   14.07    12.6   12.54   12.43   12.36   12.29
   13.12   12.53   12.44    9.13    9.11    8.83    8.75    8.57    8.36    7.41
     6.6    6.61    6.61    6.48    8.26    9.55   10.13   10.45   10.99   11.46
   11.41   10.65   11.18   11.79   12.14   11.49   11.58   13.37   14.96    17.9
   17.56   18.34   19.32   19.67
Pier Skew, UpSta & Num, DnSta & Num=,4992.2, 2 ,4992.2, 2 , 0 , 0 , 0 ,,
       1       1
     0.7     8.5
       1       1
   -0.16    7.64
Pier Skew, UpSta & Num, DnSta & Num=,5003.5, 2 ,5003.5, 2 , 0 , 0 , 0 ,,
       1       1
    0.76    8.48
       1       1
    -0.1    7.62
BR Coef= 1 , 1 , 0 ,1.25, 0 ,,,0.8,0,2,0,
Wspro=,,,, 1 ,,,, 0 ,,,, 0 ,,,,-1 ,-1 ,-1 , 0 , 0 , 0 , 0 , 0
BC Design=,, 0 ,, 0 ,,,,,,
BR U #Sta/Elev= 75
  4555.4      16  4589.2      16  4625.4    15.8  4635.4   15.75  4659.2   15.62
  4675.4   15.06  4679.2   14.93  4689.2   14.93  4695.4   14.63  4719.2   13.46
  4725.4    13.4  4735.4   13.29  4742.2   13.22  4749.2   13.15    4763   13.98
  4832.2   13.39    4843    13.3  4860.6   12.22  4883.2   10.84    4897    9.99
  4902.2   10.01    4905      10  4914.9    9.97  4928.8    9.69    4929    9.69
  4941.2    9.67    4950    9.61  4959.1    9.54  4968.9    9.43  4976.7    9.22
  4980.3    8.27  4980.8    7.61 4980.91    7.46    4981    7.34  4981.1    7.21
  4982.4    5.48  4983.1     5.2  4988.9    1.92  4990.4    1.72  4992.2    1.69
  5000.3    1.84  5003.4    1.75  5003.5    1.75  5011.1     2.8  5013.2     6.2
 5013.79    7.16  5013.9    7.34  5014.6    8.47    5015    9.12  5033.3   10.41
  5034.7   10.51  5046.7   10.99  5052.1   11.31  5061.3   11.85  5062.6   11.89
  5078.3   12.32  5079.3   12.32  5087.6   12.29  5096.3   12.27  5105.1   11.51
  5114.5   11.99  5115.4   12.04  5125.4   12.65  5131.2      13  5139.5   12.58
  5144.1   12.35  5146.1   12.44  5146.6   12.46  5185.4   14.23  5220.2   15.82
  5290.2   18.76  5310.2   18.42  5370.2    19.2  5390.2   20.18  5458.7   20.53
BR U #Mann= 6
 4555.40     0.2  4860.6     0.1  4980.3    0.04    5015    0.08  5139.5    0.14
  5146.6     0.2
BR U Banks=4980.30,5015.00
BR D #Sta/Elev= 75
  4555.4   15.14  4589.2   15.14  4625.4   14.94  4635.4   14.89  4659.2   14.76
  4675.4    14.2  4679.2   14.07  4689.2   14.07  4695.4   13.77  4719.2    12.6
  4725.4   12.54  4735.4   12.43  4742.2   12.36  4749.2   12.29    4763   13.12
  4832.2   12.53    4843   12.44  4860.6   11.36  4883.2    9.98    4897    9.13
  4902.2    9.15    4905    9.14  4914.9    9.11  4928.8    8.83    4929    8.83
  4941.2    8.81    4950    8.75  4959.1    8.68  4968.9    8.57  4976.7    8.36
  4980.3    7.41  4980.8    6.75 4980.91     6.6    4981    6.48  4981.1    6.35
  4982.4    4.62  4983.1    4.34  4988.9    1.06  4990.4    0.86  4992.2    0.83
  5000.3    0.98  5003.4    0.89  5003.5    0.89  5011.1    1.94  5013.2    5.34
 5013.79     6.3  5013.9    6.48  5014.6    7.61    5015    8.26  5033.3    9.55
  5034.7    9.65  5046.7   10.13  5052.1   10.45  5061.3   10.99  5062.6   11.03
  5078.3   11.46  5079.3   11.46  5087.6   11.43  5096.3   11.41  5105.1   10.65
  5114.5   11.13  5115.4   11.18  5125.4   11.79  5131.2   12.14  5139.5   11.72
  5144.1   11.49  5146.1   11.58  5146.6    11.6  5185.4   13.37  5220.2   14.96
  5290.2    17.9  5310.2   17.56  5370.2   18.34  5390.2   19.32  5458.7   19.67
BR D #Mann= 6
 4555.40     0.2  4860.6     0.1  4980.3    0.04    5015    0.08  5139.5    0.14
  5146.6     0.2
BR D Banks=4980.30,5015.00

Type RM Length L Ch R = 1 ,2563.9,68.6,68.6,68.6
XS GIS Cut Line= 6
      3196372.65     13848548.41      3196184.48     13848548.42
      3196085.61     13848560.87      3196010.31     13848602.14
      3195897.92     13848662.66      3195553.25     13848869.48
BEGIN DESCRIPTION:
Downstream Section of Bridge/Culvert/Weir
END DESCRIPTION:
#Sta/Elev= 30
  4555.4   15.13  4659.2   14.75  4689.2   14.06  4719.2   12.59  4749.2   12.28
    4763   13.11    4843   12.43  4860.6   11.35    4897    9.12  4968.9    8.56
  4976.7    8.35  4980.3     7.4  4982.4    4.61  4988.9    1.05  4992.2    0.82
  5003.5    0.88  5011.1    1.93    5015    8.25  5062.6   11.02  5078.3   11.45
  5096.3    11.4  5105.1   10.64  5131.2   12.13  5139.5   11.71  5146.6   11.59
  5290.2   17.89  5310.2   17.55  5370.2   18.33  5390.2   19.31  5458.7   19.66
#Mann= 6 , 1 , 0
 4555.40     0.2       0  4860.6     0.1       0  4980.3    0.04       0
    5015    0.08       0  5139.5    0.14       0  5146.6     0.2       0
#XS Ineff= 2 , 0
       0    4970       9    5024       0       9
Bank Sta=4980.30,5015.00
Exp/Cntr=0.5,0.3

Type RM Length L Ch R = 1 ,2495.3,50.4,184.9,194.5
XS GIS Cut Line= 5
      3196416.19     13848554.58      3196129.92     13848554.58
      3195950.79     13848556.72      3195770.59     13848666.13
      3195489.56     13848807.18
BEGIN DESCRIPTION:
Cross Section 2495.3 - Interpolated
END DESCRIPTION:
#Sta/Elev= 26
  4500.8      18  4723.8    13.1  4738.8    13.7  4827.1    13.8  4842.1    13.5
  4857.1    11.9  4907.1     9.6  4962.1     8.8  4966.2     8.6  4981.2     7.6
 4983.11    5.91 4985.88     1.7  4987.7    1.11 4993.76    0.91 4999.48    1.01
 5014.03    1.39 5015.93    6.69  5031.2     8.1  5036.2       9  5086.2    11.2
  5141.2    12.9    5177    14.5    5248   16.85    5292    18.3    5342    19.9
  5491.5    20.9
#Mann= 4 , 1 , 0
 4500.80     0.1       0 4983.11    0.04       0 5015.93     0.1       0
    5248     0.2       0
Bank Sta=4983.11,5015.93
Exp/Cntr=0.5,0.3

Type RM Length L Ch R = 1 ,2310.4,78.8,78.8,78.8
XS GIS Cut Line= 5
      3196619.33     13848552.61      3196146.73     13848527.52
      3195654.79     13848506.13      3195173.55     13848479.39
      3194901.36     13848468.65
BEGIN DESCRIPTION:
Upstream Section of Bridge/Culvert/Weir
END DESCRIPTION:
#Sta/Elev= 30
  4135.3   20.15 4471.48   16.63  4488.8   14.99 4514.78   14.44 4523.44   15.16
 4566.74    15.2 4592.72   13.69  4618.7    13.2 4735.35    13.4 4778.91    7.54
 4810.69    5.88 4937.22    4.84 4983.11    6.15 4985.88    1.94 4993.76    1.15
 5014.03    1.63 5015.93    6.93  5034.9    7.51 5068.85    6.59 5105.74    8.78
 5166.71   10.41  5186.1   11.61 5194.94   16.27    5248   17.44 5359.48   16.77
  5376.8   17.68 5411.44   17.07 5472.06   18.75 5587.06   18.49 5855.35   20.05
#Mann= 4 , 1 , 0
 4135.30     0.1       0 4983.11    0.04       0 5015.93     0.1       0
    5248     0.2       0
#XS Ineff= 2 , 0
       0    4975    13.6    5017       0    13.6
Bank Sta=4983.11,5015.93
Exp/Cntr=0.5,0.3

Type RM Length L Ch R = 2 ,2271.0,,,
BEGIN DESCRIPTION:
MARKET STREET
Structure ID: N04-2
END DESCRIPTION:
Bridge Culvert--1,0,-1,-1, 0
Deck Dist Width WeirC Skew NumUp NumDn MinLoCord MaxHiCord MaxSubmerge Is_Ogee
10,58.8,3,,57,57,,,0.95,0,1,1,,
  4135.3  4402.2 4471.48  4488.8 4514.78 4523.44 4549.42 4566.74 4592.72  4618.7
 4622.77 4648.75 4735.35    4738 4744.01 4778.91  4799.9 4810.69 4842.65  4857.8
 4896.51  4918.7 4937.22 4964.75    4971 4983.11 4985.88  4987.7 4993.76 4999.48
 5014.03  5014.7 5015.93  5034.9 5050.14 5068.85  5076.5 5079.67 5105.74 5123.66
  5128.6 5143.76 5166.71  5180.8  5186.1 5194.94    5248 5255.56 5264.22 5359.48
  5376.8 5411.44 5472.06 5517.78 5587.06 5714.88 5855.35
   20.16    17.2   16.65   16.24   15.95   15.85   15.56   15.37   15.08   14.79
   14.75   14.46    13.5   13.47   13.44   13.27   13.17   13.14   13.04      13
   13.06    13.1   13.23   13.42   13.46   13.52   13.53   13.54   13.57    13.6
   13.67   13.67   13.68   13.84   13.97   14.13   14.19   14.22   14.49   14.67
   14.72   14.89   15.16   15.32   15.36   16.29   17.46   17.63   16.94   16.79
    17.7   17.09   18.77   19.02   18.51   19.31   20.06
   20.16   17.04   16.64      15   14.45   15.17   14.99   15.21    13.7   13.21
   13.27   13.77   13.41   13.08   12.32    7.55    6.45    5.89    5.71    5.54
    5.11    4.97    4.85    5.93    6.01    6.16    1.95    1.36    1.16    1.26
    1.64    3.51    6.94    7.52    7.38     6.6    7.12    7.33    8.79    9.18
    9.31    9.71   10.42   11.29   11.62   16.28   17.45   17.62   16.93   16.78
   17.69   17.08   18.76   19.01    18.5    19.3   20.06
  4135.3  4402.2 4471.48  4488.8 4514.78 4523.44 4549.42 4566.74 4592.72  4618.7
 4622.77 4648.75 4735.35    4738 4744.01 4778.91  4799.9 4810.69 4842.65  4857.8
 4896.51  4918.7 4937.22 4964.75    4971 4983.11 4985.88  4987.7 4993.76 4999.48
 5014.03  5014.7 5015.93  5034.9 5050.14 5068.85  5076.5 5079.67 5105.74 5123.66
  5128.6 5143.76 5166.71  5180.8  5186.1 5194.94    5248 5255.56 5264.22 5359.48
  5376.8 5411.44 5472.06 5517.78 5587.06 5714.88 5855.35
   20.16    17.2   16.65   16.24   15.95   15.85   15.56   15.37   15.08   14.79
   14.75   14.46    13.5   13.47   13.44   13.27   13.17   13.14   13.04      13
   13.06    13.1   13.23   13.42   13.46   13.52   13.53   13.54   13.57    13.6
   13.67   13.67   13.68   13.84   13.97   14.13   14.19   14.22   14.49   14.67
   14.72   14.89   15.16   15.32   15.36   16.29   17.46   17.63   16.94   16.79
    17.7   17.09   18.77   19.02   18.51   19.31   20.06
    18.7   15.58   15.18   13.54   12.99   13.71   13.53   13.75   12.24   11.75
   11.81   12.31   11.95   11.62   10.86    6.09    4.99    4.43    4.25    4.08
    3.65    3.51    3.39    4.47    4.55     4.7    0.49    -0.1    -0.3    -0.2
    0.18    2.05    5.48    6.06    5.92    5.14    5.66    5.87    7.33    7.72
    7.85    8.25    8.96    9.83   10.16   14.82   15.99   16.16   15.47   15.32
   16.23   15.62    17.3   17.55   17.04   17.84    18.6
BR Coef= 1 , 0 , 0 ,1.25, 0 ,,,0.8,-1,2,0,
Wspro=,,,, 1 ,,,, 0 ,,,, 0 ,,,,-1 ,-1 ,-1 , 0 , 0 , 0 , 0 , 0
Culvert=2,8.0,8.7,58.8,0.015,0.2,1.0,8,1,-0.03,4990.10,-0.05,4990.10,Culvert #1  ,0,10
Culvert=2,8.0,8.7,58.8,0.015,0.2,1.0,8,1,-0.03,5002.00,-0.05,5002.00,Culvert #2  ,0,10
BC Design=,, 0 ,, 0 ,,,,,,
BR U #Sta/Elev= 57
  4135.3   20.16  4402.2   17.04 4471.48   16.64  4488.8      15 4514.78   14.45
 4523.44   15.17 4549.42   14.99 4566.74   15.21 4592.72    13.7  4618.7   13.21
 4622.77   13.27 4648.75   13.77 4735.35   13.41    4738   13.08 4744.01   12.32
 4778.91    7.55  4799.9    6.45 4810.69    5.89 4842.65    5.71  4857.8    5.54
 4896.51    5.11  4918.7    4.97 4937.22    4.85 4964.75    5.93    4971    6.01
 4983.11    6.16 4985.88    1.95  4987.7    1.36 4993.76    1.16 4999.48    1.26
 5014.03    1.64  5014.7    3.51 5015.93    6.94  5034.9    7.52 5050.14    7.38
 5068.85     6.6  5076.5    7.12 5079.67    7.33 5105.74    8.79 5123.66    9.18
  5128.6    9.31 5143.76    9.71 5166.71   10.42  5180.8   11.29  5186.1   11.62
 5194.94   16.28    5248   17.45 5255.56   17.62 5264.22   16.93 5359.48   16.78
  5376.8   17.69 5411.44   17.08 5472.06   18.76 5517.78   19.01 5587.06    18.5
 5714.88    19.3 5855.35   20.06
BR U #Mann= 4
 4135.30     0.1 4983.11    0.04 5015.93     0.1    5248     0.2
BR U Banks=4983.11,5015.93
BR D #Sta/Elev= 57
  4135.3    18.7  4402.2   15.58 4471.48   15.18  4488.8   13.54 4514.78   12.99
 4523.44   13.71 4549.42   13.53 4566.74   13.75 4592.72   12.24  4618.7   11.75
 4622.77   11.81 4648.75   12.31 4735.35   11.95    4738   11.62 4744.01   10.86
 4778.91    6.09  4799.9    4.99 4810.69    4.43 4842.65    4.25  4857.8    4.08
 4896.51    3.65  4918.7    3.51 4937.22    3.39 4964.75    4.47    4971    4.55
 4983.11     4.7 4985.88    0.49  4987.7    -0.1 4993.76    -0.3 4999.48    -0.2
 5014.03    0.18  5014.7    2.05 5015.93    5.48  5034.9    6.06 5050.14    5.92
 5068.85    5.14  5076.5    5.66 5079.67    5.87 5105.74    7.33 5123.66    7.72
  5128.6    7.85 5143.76    8.25 5166.71    8.96  5180.8    9.83  5186.1   10.16
 5194.94   14.82    5248   15.99 5255.56   16.16 5264.22   15.47 5359.48   15.32
  5376.8   16.23 5411.44   15.62 5472.06    17.3 5517.78   17.55 5587.06   17.04
 5714.88   17.84 5855.35    18.6
BR D #Mann= 4
 4135.30     0.1 4983.11    0.04 5015.93     0.1    5248     0.2
BR D Banks=4983.11,5015.93

Type RM Length L Ch R = 1 ,2231.6,15.6,15.6,15.6
XS GIS Cut Line= 5
      3196576.52     13848486.45      3196103.93     13848461.36
      3195611.99     13848439.97      3195130.75     13848413.23
      3194858.56     13848402.49
BEGIN DESCRIPTION:
Downstream Section of Bridge/Culvert/Weir
END DESCRIPTION:
#Sta/Elev= 30
  4135.3   18.59 4471.48   15.07  4488.8   13.43 4514.78   12.88 4523.44    13.6
 4566.74   13.64 4592.72   12.13  4618.7   11.64 4735.35   11.84 4778.91    5.98
 4810.69    4.32 4937.22    3.28 4983.11    4.59 4985.88    0.38 4993.76   -0.41
 5014.03    0.07 5015.93    5.37  5034.9    5.95 5068.85    5.03 5105.74    7.22
 5166.71    8.85  5186.1   10.05 5194.94   14.71    5248   15.88 5359.48   15.21
  5376.8   16.12 5411.44   15.51 5472.06   17.19 5587.06   16.93 5855.35   18.49
#Mann= 4 , 1 , 0
 4135.30     0.1       0 4983.11    0.04       0 5015.93     0.1       0
    5248     0.2       0
#XS Ineff= 2 , 0
       0    4975    12.8    5017       0    12.6
Bank Sta=4983.11,5015.93
Exp/Cntr=0.5,0.3

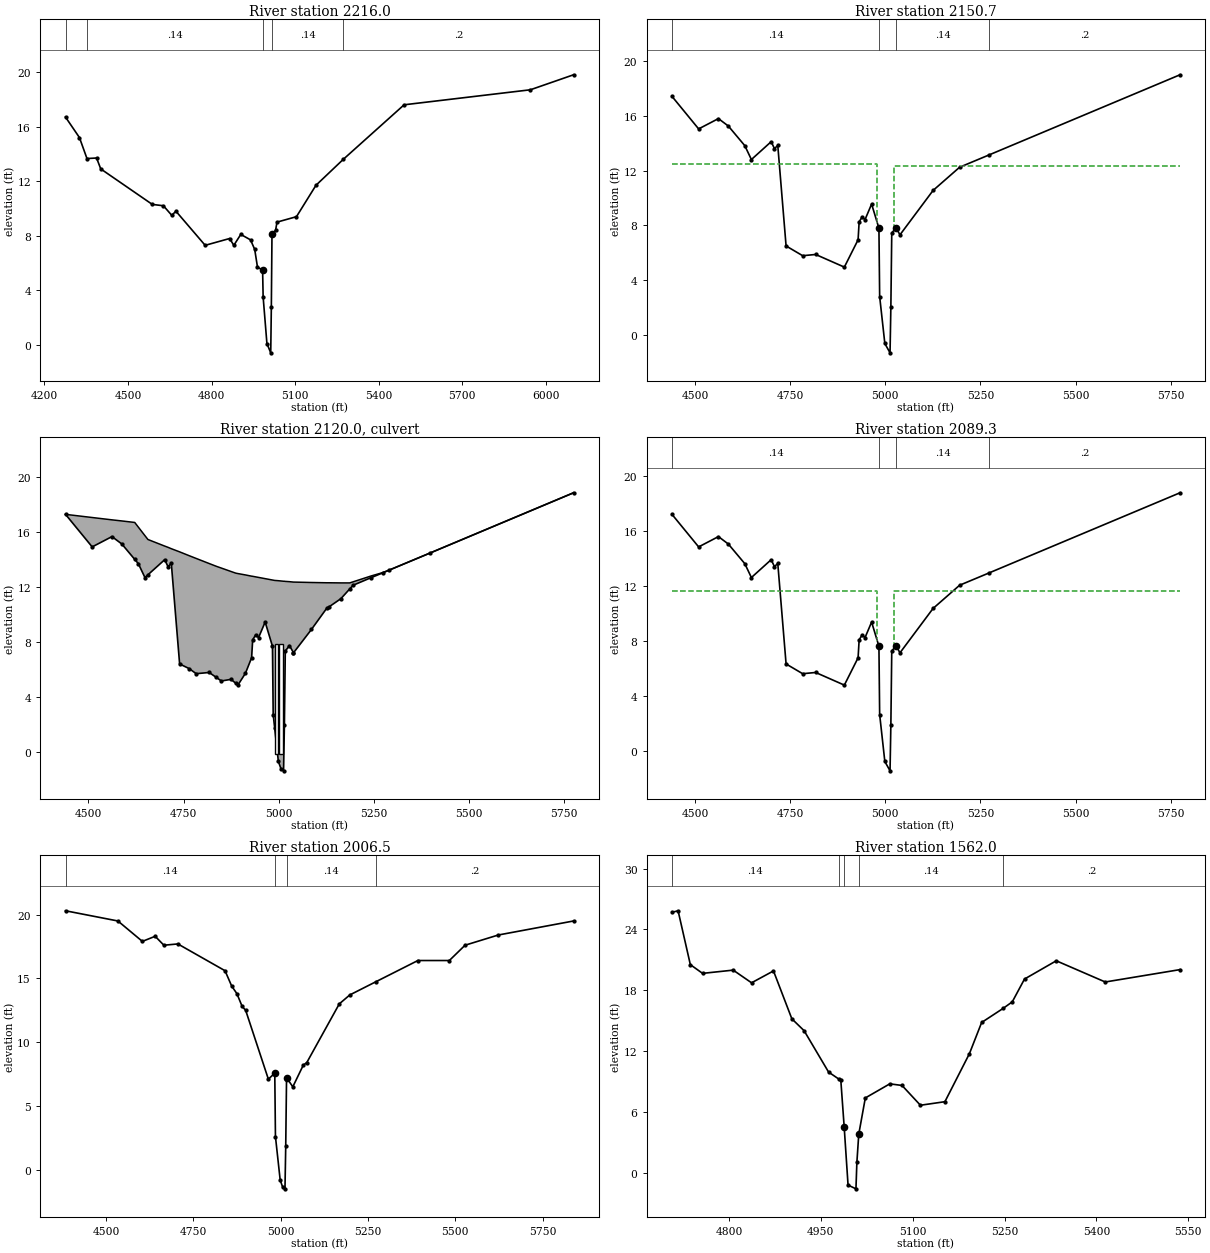
Type RM Length L Ch R = 1 ,2216.0,32.8,65.3,28.4
XS GIS Cut Line= 6
      3196420.53     13848422.55      3196357.89     13848455.96
      3195885.15     13848443.97      3195484.40     13848417.57
      3194771.69     13848386.37      3194610.21     13848423.54
BEGIN DESCRIPTION:
Cross Section 2216.0 - Interpolated
END DESCRIPTION:
#Sta/Elev= 30
  4275.5    16.7  4325.5    15.2  4352.6   13.66  4387.1    13.7  4402.1    12.9
  4587.1    10.3  4627.1    10.2  4657.1     9.5  4672.1     9.8  4777.1     7.3
    4865     7.8    4880     7.3    4905     8.1    4940     7.7    4955       7
    4965     5.7 4983.37    5.49 4985.28    3.52 4998.87     0.1 5012.56   -0.58
 5014.72    2.76 5017.06    8.13    5030     8.4    5035       9    5105     9.4
    5175    11.7    5273    13.6  5491.6    17.6    5945    18.7  6100.1    19.8
#Mann= 5 , 1 , 0
 4275.50     0.2       0  4352.6    0.14       0 4983.37    0.06       0
 5017.06    0.14       0    5273     0.2       0
Bank Sta=4983.37,5017.06
Exp/Cntr=0.5,0.3

Type RM Length L Ch R = 1 ,2150.7,61.4,61.4,61.4
XS GIS Cut Line= 5
      3196225.60     13848410.83      3195947.19     13848395.36
      3195603.82     13848376.15      3195176.42     13848356.95
      3194892.72     13848347.97
BEGIN DESCRIPTION:
Upstream Section of Bridge/Culvert/Weir
END DESCRIPTION:
#Sta/Elev= 30
 4439.78    17.4 4509.84   15.03  4561.8   15.78 4587.78   15.24 4631.08   13.81
  4648.4    12.8 4700.36    14.1 4709.02   13.59 4717.68   13.83 4739.51    6.51
 4783.07     5.8 4817.19    5.89 4892.53    4.97 4928.64    6.96 4931.41    8.27
 4939.21    8.62 4946.91    8.43 4964.15    9.56 4983.37     7.8 4985.28    2.83
 4998.87   -0.59 5012.56   -1.27 5014.72    2.07 5017.06    7.44 5027.97    7.85
 5038.62    7.32 5125.57   10.55 5195.28   12.24    5273   13.14  5774.2   18.97
#Mann= 4 , 1 , 0
 4439.78    0.14       0 4983.37    0.07       0 5027.97    0.14       0
    5273     0.2       0
#XS Ineff= 2 , 0
       0    4979    12.5    5024       0    12.3
Bank Sta=4983.37,5027.97
Exp/Cntr=0.5,0.3

Type RM Length L Ch R = 2 ,2120.0,,,
BEGIN DESCRIPTION:
OLD RAILROAD - 30 Degree Skew
Structure ID: N04-1
END DESCRIPTION:
Bridge Culvert--1,0,-1,-1, 0
Deck Dist Width WeirC Skew NumUp NumDn MinLoCord MaxHiCord MaxSubmerge Is_Ogee
10,41.4,3,,48,48,,,0.95,0,1,1,,
 4439.78 4509.84  4561.8 4587.78 4621.64 4631.08  4648.4 4656.28 4700.36 4709.02
 4717.68 4739.51 4764.71 4783.07 4817.19  4835.8 4849.14  4874.6    4887 4892.53
 4912.36 4928.64 4931.41 4939.21 4946.91 4964.15 4983.37 4985.28  4989.2 4998.87
 5005.89 5012.56 5014.72 5017.06 5027.97  5038.5 5038.62 5085.73 5125.57  5131.1
 5163.07  5186.3 5195.28  5243.1    5273  5288.9    5396  5774.2
    17.3   17.07    16.9   16.82   16.71   16.37   15.75   15.47   14.99    14.9
    14.8   14.57   14.29   14.09   13.72   13.52   13.39   13.14   13.02   12.99
   12.89    12.8   12.79   12.75   12.71   12.62   12.52   12.51   12.49   12.47
   12.45   12.43   12.43   12.42    12.4   12.37   12.37   12.34   12.32   12.32
   12.31   12.31   12.39   12.82   13.06   13.23   14.47   18.87
    17.3   14.93   15.68   15.14   14.02   13.71    12.7    12.9      14   13.49
   13.73    6.41    6.07     5.7    5.79    5.43    5.17    5.29       5    4.87
    5.73    6.86    8.17    8.52    8.33    9.46     7.7    2.73    1.74   -0.69
   -1.23   -1.37    1.97    7.34    7.75    7.23    7.22    8.92   10.45   10.55
   11.16   11.87   12.14    12.7   13.04   13.23   14.47   18.87
 4439.78 4509.84  4561.8 4587.78 4621.64 4631.08  4648.4 4656.28 4700.36 4709.02
 4717.68 4739.51 4764.71 4783.07 4817.19  4835.8 4849.14  4874.6    4887 4892.53
 4912.36 4928.64 4931.41 4939.21 4946.91 4964.15 4983.37 4985.28  4989.2 4998.87
 5005.89 5012.56 5014.72 5017.06 5027.97  5038.5 5038.62 5085.73 5125.57  5131.1
 5163.07  5186.3 5195.28  5243.1    5273  5288.9    5396  5774.2
   17.29   17.07    16.9   16.82   16.71   16.37   15.75   15.47   14.99    14.9
    14.8   14.57   14.29   14.09   13.72   13.52   13.39   13.14   13.02   12.99
   12.89    12.8   12.79   12.75   12.71   12.62   12.52   12.51   12.49   12.47
   12.45   12.43   12.43   12.42    12.4   12.37   12.37   12.34   12.32   12.32
   12.31   12.31   12.39   12.82   13.06   13.23   14.47   18.86
   17.19   14.82   15.57   15.03   13.91    13.6   12.59   12.79   13.89   13.38
   13.62     6.3    5.96    5.59    5.68    5.32    5.06    5.18    4.89    4.76
    5.62    6.75    8.06    8.41    8.22    9.35    7.59    2.62    1.63    -0.8
   -1.34   -1.48    1.86    7.23    7.64    7.12    7.11    8.81   10.34   10.44
   11.05   11.76   12.03   12.59   12.93   13.12   14.36   18.76
BR Coef= 1 , 0 , 0 ,1.25, 0 ,,,0.8,-1,2,0,
Wspro=,,,, 1 ,,,, 0 ,,,, 0 ,,,,-1 ,-1 ,-1 , 0 , 0 , 0 , 0 , 0
Culvert=2,8.0,8.7,41.4,0.015,0.2,1.0,8,1,-0.13,4994.40,-0.35,4994.40,Culvert #1  ,0,10
Culvert=2,8.0,8.7,41.4,0.015,0.2,1.0,8,1,-0.13,5005.80,-0.35,5005.80,Culvert #2  ,0,10
BC Design=,, 0 ,, 0 ,,,,,,
BR U #Sta/Elev= 48
 4439.78    17.3 4509.84   14.93  4561.8   15.68 4587.78   15.14 4621.64   14.02
 4631.08   13.71  4648.4    12.7 4656.28    12.9 4700.36      14 4709.02   13.49
 4717.68   13.73 4739.51    6.41 4764.71    6.07 4783.07     5.7 4817.19    5.79
  4835.8    5.43 4849.14    5.17  4874.6    5.29    4887       5 4892.53    4.87
 4912.36    5.73 4928.64    6.86 4931.41    8.17 4939.21    8.52 4946.91    8.33
 4964.15    9.46 4983.37     7.7 4985.28    2.73  4989.2    1.74 4998.87   -0.69
 5005.89   -1.23 5012.56   -1.37 5014.72    1.97 5017.06    7.34 5027.97    7.75
  5038.5    7.23 5038.62    7.22 5085.73    8.92 5125.57   10.45  5131.1   10.55
 5163.07   11.16  5186.3   11.87 5195.28   12.14  5243.1    12.7    5273   13.04
  5288.9   13.23    5396   14.47  5774.2   18.87
BR U #Mann= 4
 4439.78    0.14 4983.37    0.07 5027.97    0.14    5273     0.2
BR U Banks=4983.37,5027.97
BR D #Sta/Elev= 48
 4439.78   17.19 4509.84   14.82  4561.8   15.57 4587.78   15.03 4621.64   13.91
 4631.08    13.6  4648.4   12.59 4656.28   12.79 4700.36   13.89 4709.02   13.38
 4717.68   13.62 4739.51     6.3 4764.71    5.96 4783.07    5.59 4817.19    5.68
  4835.8    5.32 4849.14    5.06  4874.6    5.18    4887    4.89 4892.53    4.76
 4912.36    5.62 4928.64    6.75 4931.41    8.06 4939.21    8.41 4946.91    8.22
 4964.15    9.35 4983.37    7.59 4985.28    2.62  4989.2    1.63 4998.87    -0.8
 5005.89   -1.34 5012.56   -1.48 5014.72    1.86 5017.06    7.23 5027.97    7.64
  5038.5    7.12 5038.62    7.11 5085.73    8.81 5125.57   10.34  5131.1   10.44
 5163.07   11.05  5186.3   11.76 5195.28   12.03  5243.1   12.59    5273   12.93
  5288.9   13.12    5396   14.36  5774.2   18.76
BR D #Mann= 4
 4439.78    0.14 4983.37    0.07 5027.97    0.14    5273     0.2
BR D Banks=4983.37,5027.97

Type RM Length L Ch R = 1 ,2089.3,82.8,82.8,82.8
XS GIS Cut Line= 5
      3196186.05     13848363.86      3195907.65     13848348.40
      3195564.28     13848329.19      3195136.88     13848309.99
      3194853.17     13848301.00
BEGIN DESCRIPTION:
Downstream Section of Bridge/Culvert/Weir
END DESCRIPTION:
#Sta/Elev= 30
 4439.78   17.19 4509.84   14.82  4561.8   15.57 4587.78   15.03 4631.08    13.6
  4648.4   12.59 4700.36   13.89 4709.02   13.38 4717.68   13.62 4739.51     6.3
 4783.07    5.59 4817.19    5.68 4892.53    4.76 4928.64    6.75 4931.41    8.06
 4939.21    8.41 4946.91    8.22 4964.15    9.35 4983.37    7.59 4985.28    2.62
 4998.87    -0.8 5012.56   -1.48 5014.72    1.86 5017.06    7.23 5027.97    7.64
 5038.62    7.11 5125.57   10.34 5195.28   12.03    5273   12.93  5774.2   18.76
#Mann= 4 , 1 , 0
 4439.78    0.14       0 4983.37    0.07       0 5027.97    0.14       0
    5273     0.2       0
#XS Ineff= 2 , 0
       0    4979    11.6    5024       0    11.6
Bank Sta=4983.37,5027.97
Exp/Cntr=0.5,0.3

Type RM Length L Ch R = 1 ,2006.5,470.6,444.5,427.4
XS GIS Cut Line= 5
      3195886.87     13847816.38      3195891.90     13847999.65
      3195733.67     13848192.00      3195457.56     13848328.51
      3194744.25     13848305.39
BEGIN DESCRIPTION:
Cross Section 2006.5 - Interpolated
END DESCRIPTION:
#Sta/Elev= 30
  4384.4    20.3  4534.4    19.5  4604.4    17.9    4641    18.3    4666    17.6
    4706    17.7    4841    15.6    4860    14.4    4875    13.8    4890    12.8
    4900    12.5    4965     7.1 4983.37    7.57 4985.28     2.6 4998.87   -0.82
 5005.89   -1.36 5012.56    -1.5 5014.72    1.84 5017.06    7.21    5035     6.5
    5065     8.2    5075     8.4    5168      13    5198    13.7    5273   14.74
    5393    16.4    5483    16.4    5528    17.6    5623    18.4  5838.5    19.5
#Mann= 4 , 1 , 0
 4384.40    0.14       0 4983.37    0.06       0 5017.06    0.14       0
    5273     0.2       0
Bank Sta=4983.37,5017.06
Exp/Cntr=0.3,0.1

Type RM Length L Ch R = 1 ,1562.0,571.5,626,680.2
XS GIS Cut Line= 4
      3195405.56     13847741.39      3195319.93     13847898.86
      3194988.57     13848220.61      3194810.65     13848283.43
BEGIN DESCRIPTION:
Cross Section 1562-Interpolated
END DESCRIPTION:
#Sta/Elev= 30
  4706.8   25.69  4716.8   25.84  4736.8   20.53  4756.8   19.67  4806.8   19.99
  4836.8   18.74  4872.6   19.91  4902.6   15.19  4922.6   14.02  4962.6    9.94
  4979.1    9.26  4982.6    9.12  4988.1    4.51  4994.4    -1.2  5007.3   -1.57
  5008.8    1.03  5011.9    3.82  5022.6    7.39  5062.6    8.78  5082.6    8.62
  5112.6    6.67  5152.6    7.02  5192.6   11.75  5212.6   14.83  5247.5   16.21
  5262.6   16.86  5282.6   19.11  5334.5   20.91  5414.5   18.82  5536.6   20.04
#Mann= 5 , 1 , 0
 4706.80    0.14       0  4979.1    0.14       0  4988.1    0.06       0
  5011.9    0.14       0  5247.5     0.2       0
Bank Sta=4988.10,5011.90
Exp/Cntr=0.3,0.1

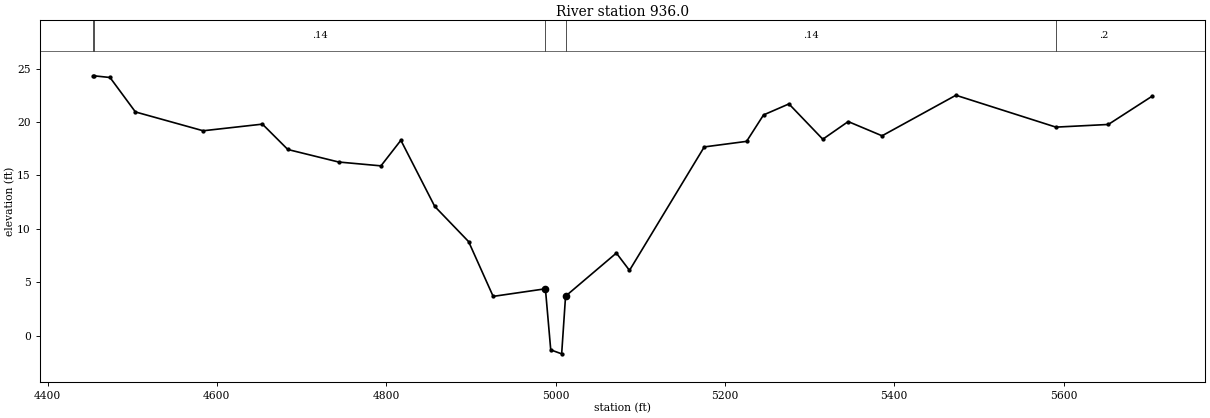
Type RM Length L Ch R = 1 ,936.0,0,0,0
XS GIS Cut Line= 5
      3195427.75     13847634.87      3195087.98     13847467.78
      3194729.72     13847467.78      3194590.69     13847719.09
      3194435.27     13847884.54
BEGIN DESCRIPTION:
Cross Section    936.0
Located At: 2ND XS DS MARKET
END DESCRIPTION:
#Sta/Elev= 30
  4453.8   24.32  4454.4   24.32  4473.8   24.16  4503.8   20.94  4583.8   19.18
  4653.8    19.8  4683.8   17.43  4743.8   16.26  4793.8    15.9  4817.3   18.29
  4857.3   12.11  4897.3    8.82  4926.3     3.7    4988    4.41  4994.3    -1.3
  5007.2   -1.67  5011.8    3.72  5071.8    7.75  5087.3    6.13  5175.6   17.67
  5225.6   18.19  5245.6   20.66  5275.6   21.69  5315.6   18.39  5345.6   20.04
  5385.6   18.71  5472.8    22.5  5590.9   19.52  5652.8   19.77  5704.9   22.43
#Mann= 5 , 1 , 0
 4453.80     0.2       0  4454.4    0.14       0    4988    0.06       0
  5011.8    0.14       0  5590.9     0.2       0
Bank Sta=4988.00,5011.80
Exp/Cntr=0.3,0.1

Chan Stop Cuts=-1